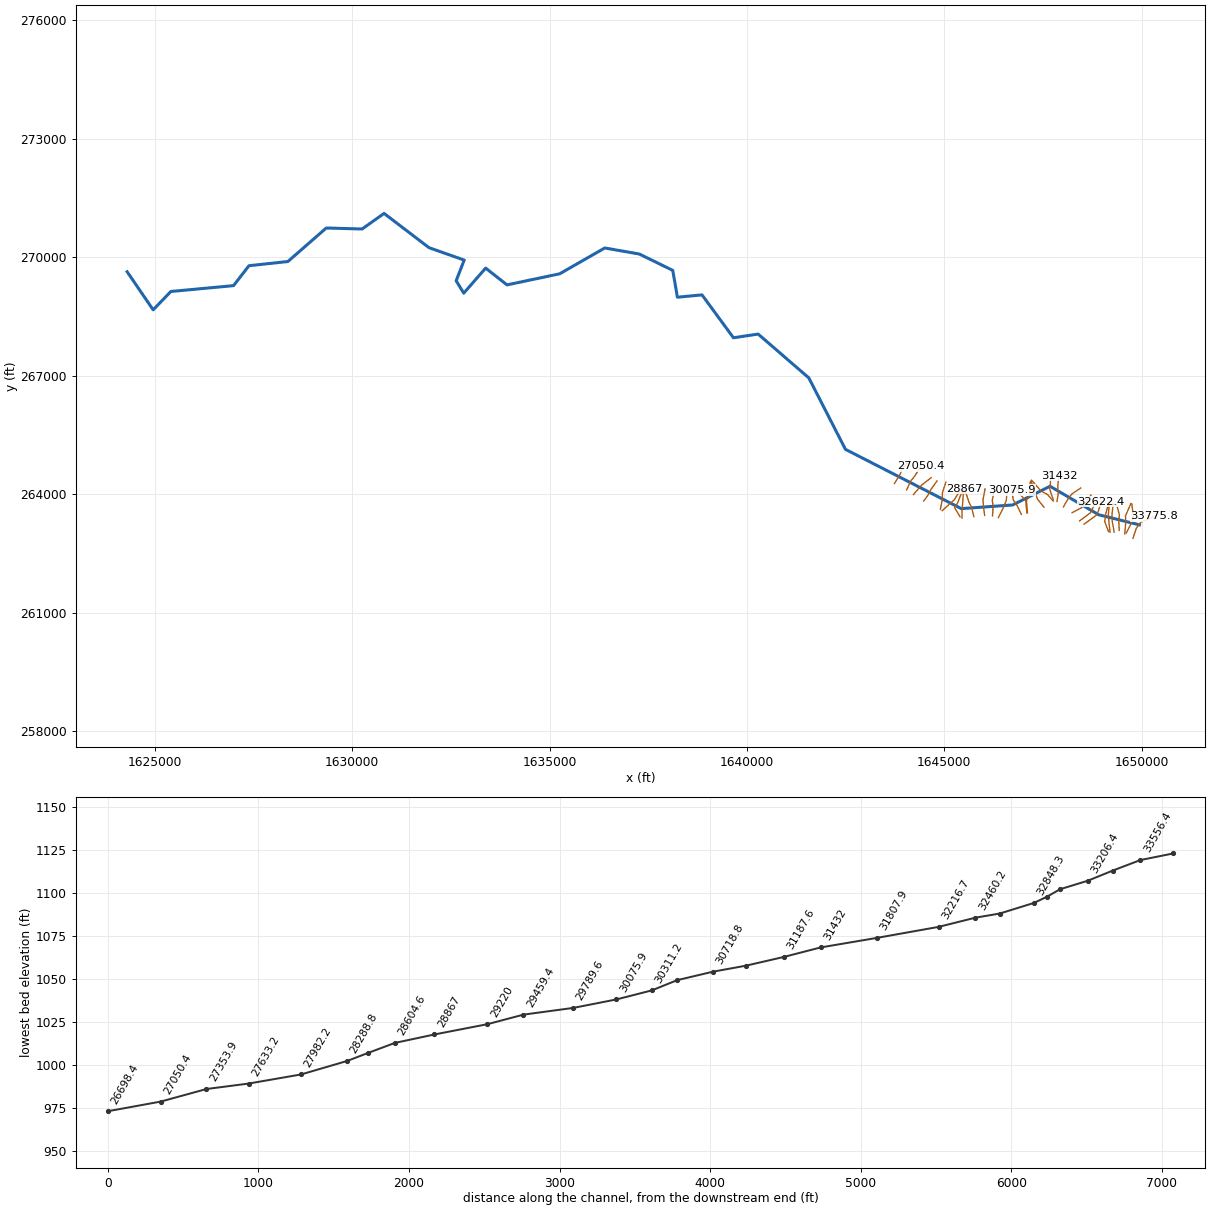
--- dmsfrk.prj (project) ---

Proj Title=dmsfrk
Current Plan=p01
Default Exp/Contr=0,0
English Units
Geom File=g01
Flow File=f01
Plan File=p01
BEGIN DESCRIPTION:
END DESCRIPTION:
DSS Export Rating Curves= 0
DSS Export Rating Curve Sorted= 0
DSS Export Volume Flow Curves= 0
DXF OffsetX= 0
DXF OffsetY= 0
DXF ScaleX= 0
DXF ScaleY= 0

--- dmsfrk.p01 (plan) ---

Plan Title=Floodplain
Program Version=4.00
Geom File=g01
Flow File=f01
K Sum by GR=0
Std Step Tol=0.01
Critical Tol=0.01
Num of Std Step Trials=20
Max Error Tol=0.3
Flow Tol Ratio=0.001
Split Flow NTrial=30
Split Flow Tol=0.02
Split Flow Ratio=0.02
Log Output Level=0
Friction Slope Method=1
Unsteady Friction Slope Method=2
Unsteady Bridges Friction Slope Method=1
Global Log Level=0
CheckData=False
Run HTab=0
Run UNet=0
Run PostProcess=0
UNET Theta=0
UNET Theta Warmup=0
UNET ZTol=0
UNET ZSATol=0
UNET MxIter=0
UNET MaxInSteps=0
UNET DtIC=0
UNET DtMin=0
UNET MaxCRTS=0
UNET WFStab=0
UNET SFStab=0
UNET WFX=0
UNET SFX=0
UNET DSS MLevel=0
UNET DZMax Abort=0
UNET Convert EG Bridges=0
UNET Use Existing IB Tables=0
UNET Froude Limit=0
UNET Froude Power=0
Write IC File=0
Echo Input=False
Echo Output=False
Write Detailed=0

--- dmsfrk.f01 (steady flow) ---

Flow Title=NFF Regression Equation
Program Version=4.00
Number of Profiles=1
Profile Names=P100yr
River Rch & RM=dmsfrk,Main      ,33775.8
     355
River Rch & RM=dmsfrk,Main      ,33556.4
     355
River Rch & RM=dmsfrk,Main      ,33373
     442
River Rch & RM=dmsfrk,Main      ,32460.2
     474
River Rch & RM=dmsfrk,Main      ,30937
     512
River Rch & RM=dmsfrk,Main      ,28867
     566
River Rch & RM=dmsfrk,Main      ,28288.8
     613
River Rch & RM=dmsfrk,Main      ,25757.4
     672
River Rch & RM=dmsfrk,Main      ,24710.3
     744
River Rch & RM=dmsfrk,Main      ,23195
     767
River Rch & RM=dmsfrk,Main      ,21622.3
     850
River Rch & RM=dmsfrk,Main      ,21166.9
    1374
River Rch & RM=dmsfrk,Main      ,20994.5
    1534
River Rch & RM=dmsfrk,Main      ,16282.2
    1667
River Rch & RM=dmsfrk,Main      ,15948.9
    1960
River Rch & RM=dmsfrk,Main      ,15016.4
    1969
River Rch & RM=dmsfrk,Main      ,9216.1
    2187
Boundary for River Rch & Prof#=dmsfrk,Main      ,1
Up Type=0
Dn Type=3
Dn Slope=0.010512

--- dmsfrk.g01 (geometry) ---

Geom Title=USGS 10m DEM
Program Version=4.00

River Reach=dmsfrk          ,Main
Reach XY= 30
     1649943.792      263226.405     1648910.202       263482.22
     1647678.385        264203.3     1646732.211      263730.117
     1645430.086      263637.238     1642495.266       265137.21
     1641566.731      266946.151     1640283.406      268054.637
     1639657.685      267961.092     1638861.041      269046.518
     1638237.624      268987.222      1638120.15      269666.456
     1637271.177      270080.978     1636397.236      270233.078
      1635257.38       269580.82       1633921.3      269298.865
      1633379.88      269724.037      1632824.36      269090.185
     1632632.375      269404.409     1632836.057      269927.157
     1631944.345      270240.912     1630805.775      271108.222
     1630249.799       270713.66     1629341.834      270739.214
     1628369.187      269891.142     1627382.165      269784.135
     1626991.987       269280.52     1625404.138       269132.35
     1624955.398      268667.882     1624296.354      269632.109

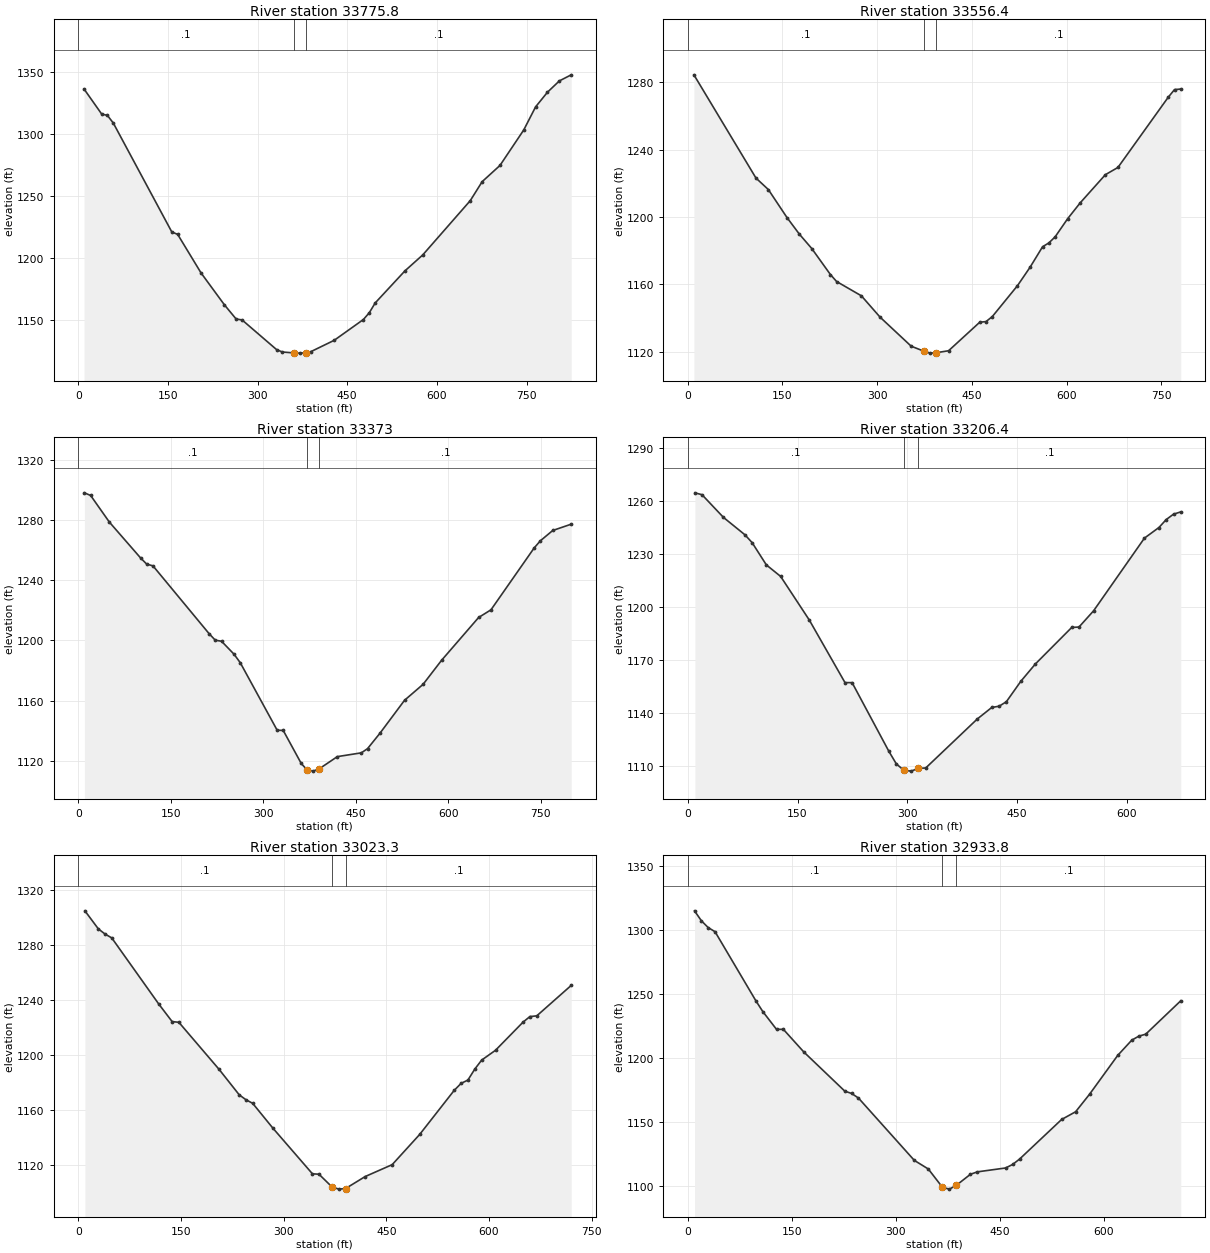
Type RM Length L Ch R = 1 ,33775.8 ,209.6,219.4,229.2
XS GIS Cut Line= 4
     1649779.459      262886.134     1649867.547      263145.679
     1649977.657      263291.968     1650314.278      263439.829
#Sta/Elev= 30
     9.8 1336.05    39.2 1315.92    48.9 1314.75    58.7 1308.64   156.6 1220.79
   166.4 1218.84   205.6  1187.7   244.7 1161.98   264.3 1150.55   274.1 1149.88
   331.9 1125.93   341.5    1124   360.5 1123.27   370.5 1123.09   380.5 1123.35
   389.7 1124.39   428.3 1133.43   477.1 1150.19     487 1155.67   496.9 1163.58
   546.6 1189.41   576.4 1202.27   655.9 1246.04   675.8 1261.35   705.6 1274.43
   745.4 1303.06   765.2 1321.66   785.1  1333.5     805 1342.61   824.8 1347.49
#Mann= 3 , 0 , 0
       0      .1       0   360.5    .045       0   380.5      .1       0
Bank Sta=360.5,380.5
XS Rating Curve= 0 ,0
Exp/Cntr=0.3,0.1

Type RM Length L Ch R = 1 ,33556.4 ,175.8,183.4,190.9
XS GIS Cut Line= 4
     1649608.002      263016.693     1649747.999      263287.249
     1649788.897      263439.829     1649751.145      263756.002
#Sta/Elev= 30
     9.8 1284.35   108.1  1223.1   127.7 1216.28   157.2 1199.68   176.9 1189.79
   196.5 1181.28     226 1165.86   235.8 1161.72   275.1 1153.22   304.6  1140.6
     354 1123.32   373.6 1120.45   383.6 1119.22   393.6 1119.46   413.2 1120.63
   462.6 1137.57   472.5 1137.93   482.5 1140.92   522.3 1159.22   542.2 1170.13
   562.1 1182.34   572.1 1184.62     582 1188.23   601.9 1199.02   621.8 1208.43
   661.6  1225.1   681.5  1229.4   761.1 1271.03   771.1 1275.59     781 1275.91
#Mann= 3 , 0 , 0
       0      .1       0   373.6    .045       0   393.6      .1       0
Bank Sta=373.6,393.6
XS Rating Curve= 0 ,0
Exp/Cntr=0.3,0.1

Type RM Length L Ch R = 1 ,33373   ,169.7,166.7,163.6
XS GIS Cut Line= 4
     1649571.823      262997.817     1649596.991      263299.833
     1649590.699      263455.559      1649727.55      263767.013
#Sta/Elev= 30
    10.1 1297.96    20.2 1296.19    50.5 1278.53     101 1254.76   111.1 1250.59
   121.2 1249.45   212.1 1204.44   222.2 1200.07   232.3 1199.38   252.6 1190.76
   262.7  1185.1   322.5 1140.26   332.3 1140.14   361.5 1118.21     371 1113.89
     381  1113.1     391 1114.73     420 1122.73   458.9 1125.25   468.9    1128
   488.9 1138.17     529 1160.19     559 1170.76     589 1186.74     649 1215.16
     669 1220.24   739.1 1261.39   749.1  1266.1   769.1 1272.94   799.1 1277.14
#Mann= 3 , 0 , 0
       0      .1       0     371    .045       0     391      .1       0
Bank Sta=371,391
XS Rating Curve= 0 ,0
Exp/Cntr=0.3,0.1

Type RM Length L Ch R = 1 ,33206.4 ,180,183.1,186.1
XS GIS Cut Line= 4
     1649431.468      263084.854      1649421.53      263309.161
     1649435.727       263479.52     1649363.324      263747.837
#Sta/Elev= 30
     9.8 1264.86    19.5  1263.8    48.8 1250.93    78.1 1241.09    87.9 1236.67
   107.4 1224.01   126.9 1217.49     166  1192.8   214.8 1157.31   224.5  1157.3
   274.8 1118.32   284.9 1111.26     295 1107.69     305 1107.15     315 1108.68
   325.1 1108.95   395.5  1136.7   415.3 1143.24   425.3 1143.93   435.2 1146.48
     455 1158.08   474.9 1167.91   524.5 1188.58   534.4 1188.81   554.3 1197.98
   623.8  1239.2   643.6 1245.21   653.5  1249.7   663.5 1252.76   673.4 1254.05
#Mann= 3 , 0 , 0
       0      .1       0     295    .045       0     315      .1       0
Bank Sta=295,315
XS Rating Curve= 0 ,0
Exp/Cntr=0.3,0.1

Type RM Length L Ch R = 1 ,33023.3 ,88.8,89.5,90.2
XS GIS Cut Line= 4
     1649302.841      263041.861     1649254.078      263321.855
     1649247.786      263476.008     1649277.673      263756.002
#Sta/Elev= 30
     9.8 1305.05    29.4 1291.91    39.2 1288.13      49 1285.33   117.6 1237.17
   137.2 1224.33     147 1223.82   205.8  1189.5   235.2 1170.95     245 1167.38
   254.8 1164.78   284.2 1146.77   342.1  1113.4   351.7 1113.09   370.6 1103.87
   380.6 1102.23   390.6 1102.68   419.2 1111.41   458.6 1120.07   498.8 1142.11
   549.1 1174.16   559.2 1179.28   569.2 1181.72   579.3 1189.74   589.3 1196.27
   609.5 1203.42   649.7 1223.92   659.7 1227.97   669.8 1228.52   720.1 1250.71
#Mann= 3 , 0 , 0
       0      .1       0   370.6    .045       0   390.6      .1       0
Bank Sta=370.6,390.6
XS Rating Curve= 0 ,0
Exp/Cntr=0.3,0.1

Type RM Length L Ch R = 1 ,32933.8 ,90.3,85.5,80.7
XS GIS Cut Line= 4
     1649199.023      263040.288     1649169.136      263304.552
     1649156.552      263496.457     1649178.574      263748.137
#Sta/Elev= 30
     9.8 1315.27    19.7  1307.5    29.5 1302.17    39.4 1298.95    98.5 1244.74
   108.3  1236.5     128 1222.65   137.9 1222.65   167.4 1204.95   226.5 1174.33
   236.4 1172.51   246.2 1168.94   326.7 1120.24   346.9 1113.49   367.3 1099.17
   377.3 1097.76   387.3 1100.73   407.7 1109.39   417.8 1111.27   458.3 1114.29
   468.4 1117.01   478.5 1121.25   539.1 1152.19   559.3 1158.23   579.5    1172
     620 1202.28   640.2 1214.16   650.3 1217.28   660.4 1218.88   710.9 1244.97
#Mann= 3 , 0 , 0
       0      .1       0   367.3    .045       0   387.3      .1       0
Bank Sta=367.3,387.3
XS Rating Curve= 0 ,0
Exp/Cntr=0.3,0.1

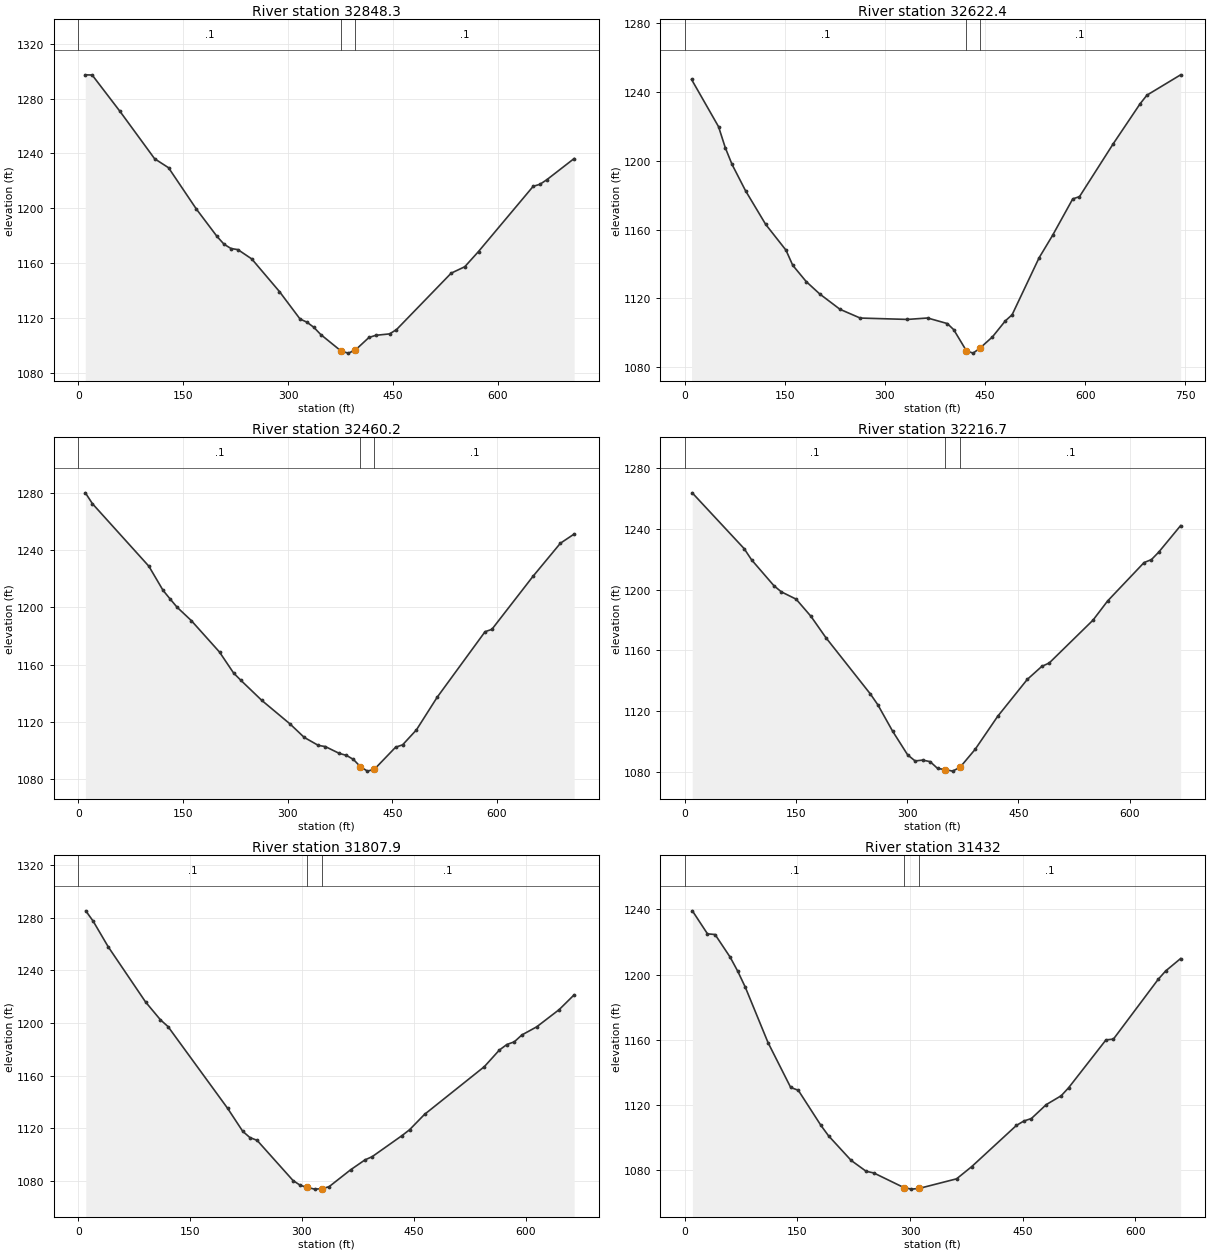
Type RM Length L Ch R = 1 ,32848.3 ,235.6,225.9,216.3
XS GIS Cut Line= 4
     1649159.698      263057.591     1649063.745      263307.698
      1649087.34      263493.311     1649153.406      263738.699
#Sta/Elev= 30
     9.9 1297.33    19.8 1297.19    59.5  1270.7   109.1 1236.08     129 1229.53
   168.7 1199.44   198.4 1179.34   208.4 1173.69   218.3 1170.57   228.2 1169.75
     248 1162.97   287.6 1139.16   317.1  1119.1     327 1116.77   336.8 1113.05
   346.7 1107.78   376.1 1095.61   386.1 1094.21   396.1 1096.41   415.6 1105.63
   425.4 1107.21   445.1 1108.25     455 1111.36   533.2 1152.56   552.7 1157.28
   572.3 1168.37   650.5 1215.95   660.2 1217.44     670 1220.77   709.1 1236.24
#Mann= 3 , 0 , 0
       0      .1       0   376.1    .045       0   396.1      .1       0
Bank Sta=376.1,396.1
XS Rating Curve= 0 ,0
Exp/Cntr=0.3,0.1

Type RM Length L Ch R = 1 ,32622.4 ,160.7,162.2,163.8
XS GIS Cut Line= 4
      1648541.51      263244.778     1648845.099      263463.424
     1648897.008      263556.231     1648972.511      263807.911
#Sta/Elev= 30
    10.1 1247.41    50.6 1219.88    60.7 1207.64    70.8 1197.94      91 1182.64
   121.3 1162.98   151.7 1147.99   161.8  1139.2     182 1129.71   202.2 1122.53
   232.6 1113.59   262.9 1108.49   333.7 1107.69     364 1108.52   393.5 1105.28
   403.1 1101.72   422.1 1089.42   432.1 1088.07   442.1 1090.86   461.1 1097.51
   480.5 1106.87   490.6 1110.39     531 1143.53   551.2 1156.58   581.5 1177.86
   591.6 1179.16   642.2 1209.96   682.6 1233.31   692.7 1238.24   743.2 1250.08
#Mann= 3 , 0 , 0
       0      .1       0   422.1    .045       0   442.1      .1       0
Bank Sta=422.1,442.1
XS Rating Curve= 0 ,0
Exp/Cntr=0.3,0.1

Type RM Length L Ch R = 1 ,32460.2 ,247.5,243.5,239.4
XS GIS Cut Line= 4
     1648428.254      263326.574     1648703.529      263532.636
     1648760.157      263650.611      1648871.84      263858.247
#Sta/Elev= 30
    10.1 1279.99    20.2  1272.4   101.1 1228.72   121.4 1211.88   131.5 1205.87
   141.6 1200.06   161.8 1190.82   202.3  1168.8   222.5 1154.15   232.6 1149.21
   262.9 1135.04   303.4 1118.57   323.6 1109.23   343.9 1103.61   353.9 1102.79
   374.1 1097.99   384.1 1096.66   394.2  1093.8   404.3 1088.69   414.3 1085.64
   424.3 1086.98   454.6 1102.33   464.7 1104.01   484.5 1114.46     514 1137.09
   582.8    1183   592.6 1184.66   651.5 1221.67   690.8  1244.8   710.5  1251.2
#Mann= 3 , 0 , 0
       0      .1       0   404.3    .045       0   424.3      .1       0
Bank Sta=404.3,424.3
XS Rating Curve= 0 ,0
Exp/Cntr=0.3,0.1

Type RM Length L Ch R = 1 ,32216.7 ,410.2,408.8,407.4
XS GIS Cut Line= 4
     1648237.922      263534.209     1648485.796      263665.124
     1648578.267      263798.052     1648716.113      263977.794
#Sta/Elev= 30
      10 1263.82    80.1 1226.99    90.1 1219.63   120.1 1202.64   130.1 1198.56
   150.2 1193.69   170.2 1182.36   190.2 1168.39   250.3 1131.19   260.3 1124.11
   280.3 1106.66   300.6 1091.01   310.7 1087.01   320.8 1087.58   330.9 1086.56
     341 1082.07   351.3 1081.29   361.3  1080.3   371.3 1082.85   391.6 1094.64
     422 1116.42   461.9 1140.75   481.6 1149.39   491.5 1151.58   550.6 1179.85
   570.3 1192.51   619.5 1217.84   629.4 1219.78   639.2 1224.68   668.8 1242.21
#Mann= 3 , 0 , 0
       0      .1       0   351.3    .045       0   371.3      .1       0
Bank Sta=351.3,371.3
XS Rating Curve= 0 ,0
Exp/Cntr=0.3,0.1

Type RM Length L Ch R = 1 ,31807.9 ,357.9,375.9,393.9
XS GIS Cut Line= 4
     1648017.702      263680.498     1648126.239      263872.404
     1648233.203      264009.254     1648458.141      264160.262
#Sta/Elev= 30
      10  1285.1      20 1277.16    40.1 1257.79    90.2 1215.93   110.2 1202.36
   120.3 1197.27   200.4  1135.1   220.5 1117.81   230.1 1113.06   239.8 1110.92
     288 1080.43   297.7 1076.81     307  1075.2     317  1073.9     327 1074.23
   336.3 1075.73   365.2 1088.56   384.5 1096.09   394.2 1098.55   434.3 1114.57
   444.3 1118.97   464.4 1130.63   544.7 1166.89   564.7 1179.41   574.8 1183.65
   584.8 1185.68   594.9 1190.88   614.9 1197.08     645 1210.14   665.1 1221.36
#Mann= 3 , 0 , 0
       0      .1       0     307    .045       0     327      .1       0
Bank Sta=307,327
XS Rating Curve= 0 ,0
Exp/Cntr=0.3,0.1

Type RM Length L Ch R = 1 ,31432   ,248.1,244.4,239.7
XS GIS Cut Line= 4
     1647854.111      263817.349      1647885.57      264006.108
     1647874.559      264196.441       1647901.3      264473.289
#Sta/Elev= 30
    10.1 1239.08    30.2 1224.96    40.3 1224.55    60.4 1210.64    70.5 1202.01
    80.6 1192.18   110.8 1158.24     141 1130.69   151.1 1128.97   181.3 1107.38
   191.4 1101.02   221.5 1085.92   241.5 1079.24   251.6 1078.24   291.7 1069.25
   301.7  1068.3   311.7  1068.7   361.9 1074.62     382  1082.1   441.6 1107.41
   451.5 1110.11   461.5 1111.63   481.3 1120.17   501.2 1125.61   511.1 1130.53
   560.8 1159.88   570.7 1160.35   630.3 1197.02   640.3  1202.2   660.2  1209.8
#Mann= 3 , 0 , 0
       0      .1       0   291.7    .045       0   311.7      .1       0
Bank Sta=291.7,311.7
XS Rating Curve= 0 ,0
Exp/Cntr=0.3,0.1

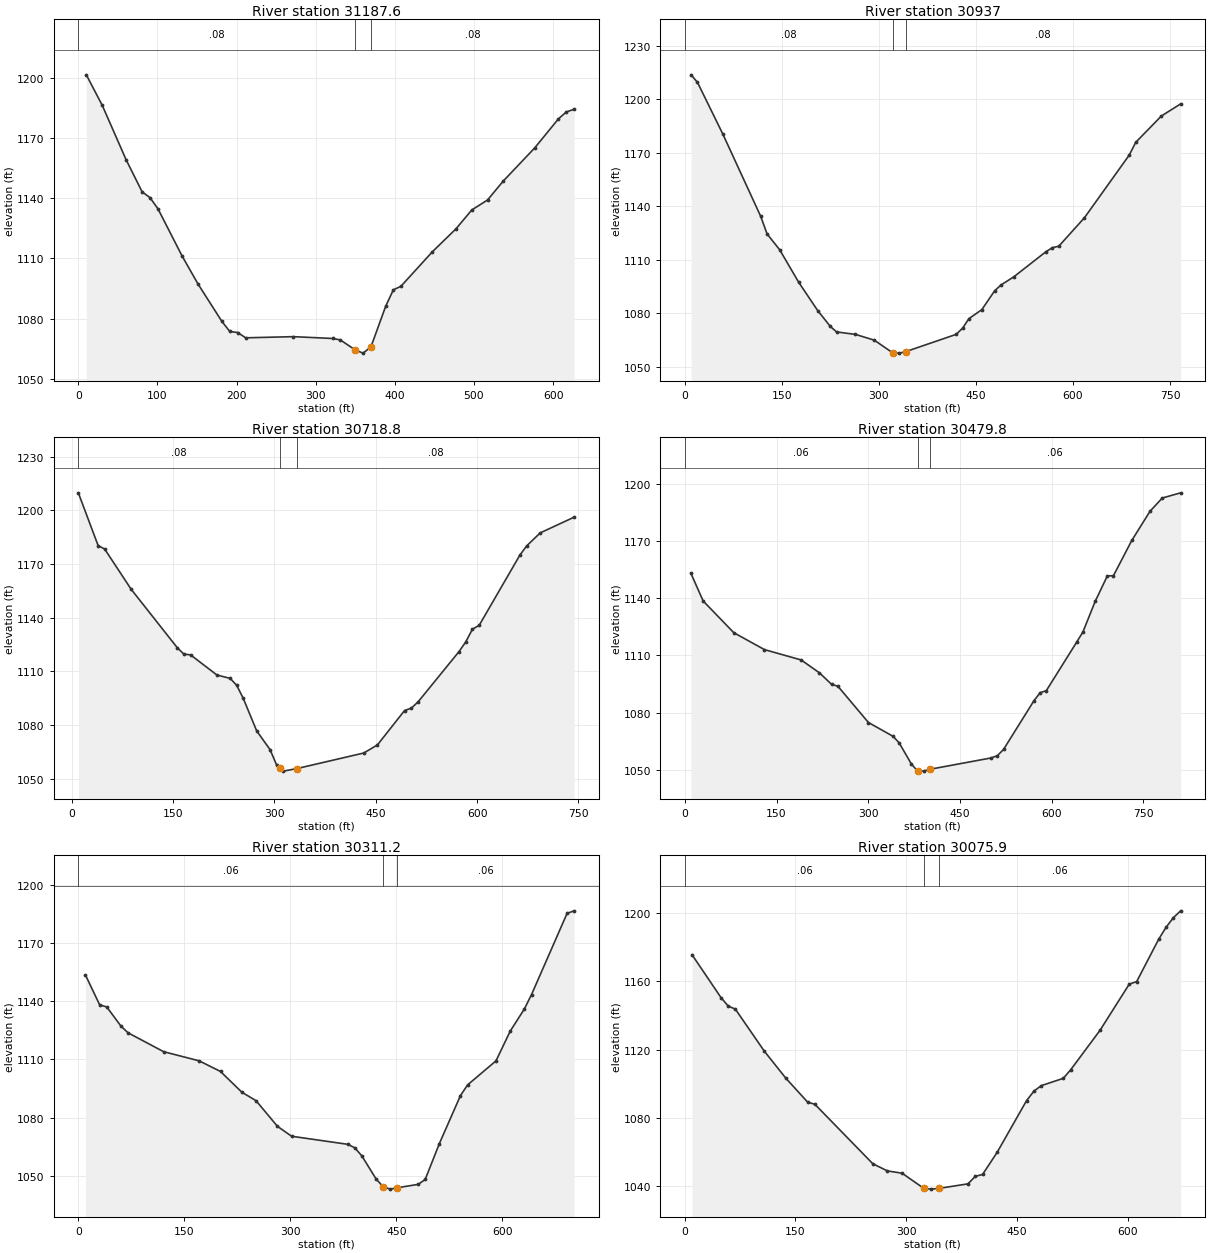
Type RM Length L Ch R = 1 ,31187.6 ,220,250.6,281.6
XS GIS Cut Line= 4
     1647760.523      263858.571     1647665.405      264145.343
      1647685.28      264248.978     1647696.638      264467.607
#Sta/Elev= 30
    10.1 1201.63    30.2 1186.42    60.4 1159.24    80.6 1143.26    90.6 1140.34
   100.7 1134.73   130.9  1111.4   151.1 1097.34   181.3 1078.66   191.4 1073.56
   201.4 1073.03   211.5  1070.4   271.9 1070.98   321.3 1070.07   330.9 1069.39
   349.7 1064.43   359.7 1062.76   369.7 1065.77   388.5 1086.23   398.1 1094.35
   407.7 1096.12   447.5 1113.37   477.3 1124.81   497.2 1134.19   517.1 1139.17
     537 1148.62   576.8 1165.18   606.7 1179.65   616.6  1183.1   626.6 1184.45
#Mann= 3 , 0 , 0
       0     .08       0   349.7    .045       0   369.7     .08       0
Bank Sta=349.7,369.7
XS Rating Curve= 0 ,0
Exp/Cntr=0.3,0.1

Type RM Length L Ch R = 1 ,30937   ,235.8,218.2,201.3
XS GIS Cut Line= 4
     1647758.158      263829.933     1647616.588      263991.951
     1647446.704      264086.331     1647212.328      264355.314
#Sta/Elev= 30
     9.8 1213.61    19.6 1209.38    58.7 1180.49   117.4 1134.26   127.1  1124.5
   146.7 1115.58     176 1097.41   205.4 1081.55   224.9 1072.65   234.6 1069.57
   263.7  1068.2   292.9 1064.96   321.8 1057.75   331.8  1057.7   341.8 1058.58
   419.4 1068.21   429.3 1071.68   439.2 1077.06     459 1082.04   478.9 1092.63
   488.8  1095.9   508.6 1100.48   558.1 1114.51   568.1 1116.76     578  1117.6
   617.6 1133.51     687 1168.72   696.9 1175.77   736.5 1190.53   766.3 1197.33
#Mann= 3 , 0 , 0
       0     .08       0   321.8    .045       0   341.8     .08       0
Bank Sta=321.8,341.8
XS Rating Curve= 0 ,0
Exp/Cntr=0.3,0.1

Type RM Length L Ch R = 1 ,30718.8 ,264.1,239,213.9
XS GIS Cut Line= 4
     1647522.208      263675.779     1647363.335      263873.976
     1647306.707      264021.838     1647198.171      264334.865
#Sta/Elev= 30
     9.8 1209.88    39.1 1180.37    48.8 1178.43    87.9 1155.98   156.3 1123.22
   166.1 1119.64   175.9 1119.25   214.9 1107.98   234.5 1106.09   244.2 1102.22
     254 1094.84   273.8 1076.71   293.6 1066.23   303.5 1057.46  308.01 1055.88
   313.4 1054.21   333.2 1055.63   432.4 1064.35   452.5 1068.87   492.7 1088.12
   502.7 1089.44   512.7 1092.95     573 1120.96     583 1126.33   593.1 1133.57
   603.1 1135.75   663.3    1175   673.4  1180.2   693.5 1187.48   743.7 1196.28
#Mann= 3 , 0 , 0
     9.8     .08       0  308.01    .045       0   333.2     .08       0
Bank Sta=308.01,333.2
XS Rating Curve= 0 ,0
Exp/Cntr=0.3,0.1

Type RM Length L Ch R = 1 ,30479.8 ,135.3,168.5,201.8
XS GIS Cut Line= 4
     1647106.937      263527.917     1647080.196      263847.236
     1647161.992      263962.064     1647177.722       264311.27
#Sta/Elev= 30
      10 1153.06      30 1138.55    80.1  1121.9   130.2 1113.03   190.3 1107.59
   220.3 1100.81   240.3 1094.73   250.3 1093.84   300.4 1074.76   340.6 1067.53
   350.6 1064.09   370.8 1052.89   380.9 1049.27   390.9 1049.25   400.9 1050.22
   501.4 1056.19   511.4 1057.41   521.3 1060.61   571.3  1086.3   581.3 1090.42
   591.3 1091.47   641.2 1117.06   651.2 1122.29   671.2 1138.29   691.1 1151.68
   701.1  1151.8   731.1  1170.3     761 1185.64     781 1192.56     811 1195.29
#Mann= 3 , 0 , 0
       0     .06       0   380.9    .045       0   400.9     .06       0
Bank Sta=380.9,400.9
XS Rating Curve= 0 ,0
Exp/Cntr=0.3,0.1

Type RM Length L Ch R = 1 ,30311.2 ,238.2,235.3,232.5
XS GIS Cut Line= 4
     1647091.207      263531.063     1647062.893      263831.506
     1646916.604      264007.681     1646839.527      264160.262
#Sta/Elev= 30
    10.1 1153.43    30.2  1138.1    40.2 1137.02    60.4 1127.13    70.4 1123.71
   120.7    1114     171 1109.29   201.2 1103.82   231.4 1093.15   251.5  1088.8
   281.7 1075.63   301.8  1070.5   381.4 1066.34   391.4 1064.52   401.3 1060.34
   421.2 1048.63   431.2 1044.57   441.2 1043.29   451.2 1043.99     481 1045.74
   490.9 1048.27   510.9 1066.69   540.8 1091.41   550.9 1096.92   591.1 1109.29
   611.2 1124.57   631.3 1136.01   641.4 1143.41   691.7 1185.18   701.7 1186.47
#Mann= 3 , 0 , 0
       0     .06       0   431.2    .045       0   451.2     .06       0
Bank Sta=431.2,451.2
XS Rating Curve= 0 ,0
Exp/Cntr=0.3,0.1

Type RM Length L Ch R = 1 ,30075.9 ,310.2,286.3,262.4
XS GIS Cut Line= 4
      1646951.21      263491.738     1646850.538      263704.093
     1646746.721      263861.393     1646707.396       264106.78
#Sta/Elev= 30
     9.8  1175.7      49 1150.55    58.8 1145.54    68.5 1143.75   107.7 1119.08
   137.1 1103.09   166.5 1089.11   176.3 1087.85   254.8 1052.93   274.7  1048.7
   294.5 1047.38   324.2 1038.39   334.2 1038.02   344.2 1038.43   383.8 1041.12
   393.7 1045.52   403.6 1046.63   423.5 1059.75   463.2    1090   473.2 1095.58
   483.1 1098.79   512.9 1103.08   522.9 1108.06   562.7 1131.26   602.4 1158.42
   612.4 1159.89   642.2 1184.73   652.1 1191.69   662.1 1197.41     672 1201.47
#Mann= 3 , 0 , 0
       0     .06       0   324.2    .045       0   344.2     .06       0
Bank Sta=324.2,344.2
XS Rating Curve= 0 ,0
Exp/Cntr=0.3,0.1

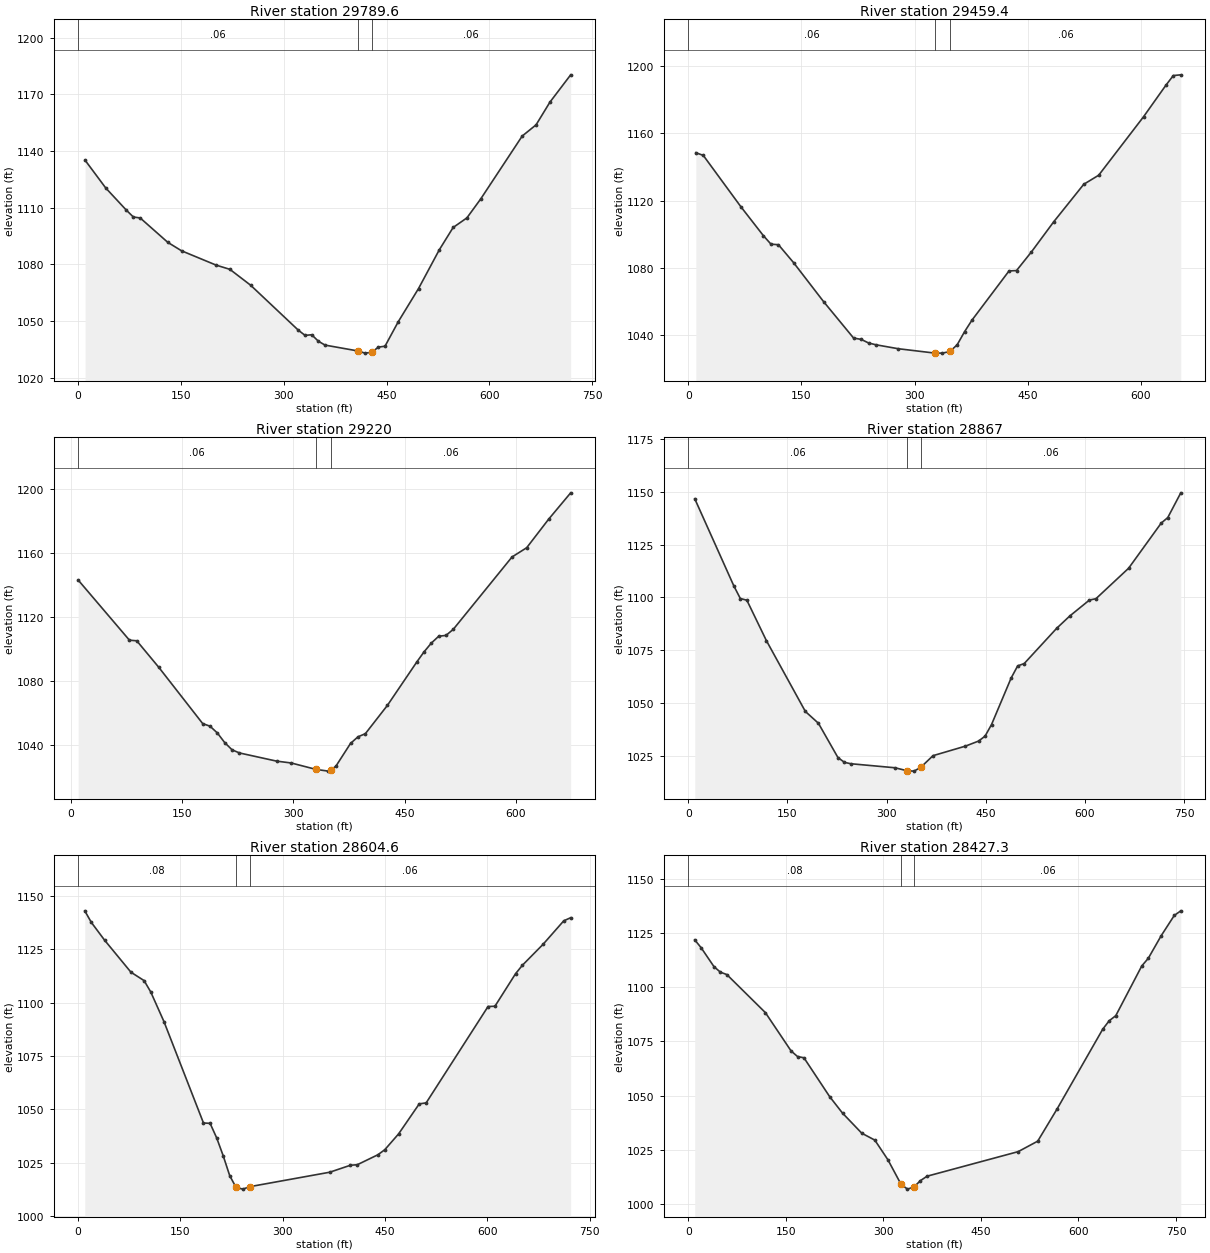
Type RM Length L Ch R = 1 ,29789.6 ,317.5,330.2,343
XS GIS Cut Line= 4
     1646369.201      263409.942     1646506.052      263678.925
     1646570.545      263851.955     1646589.421      264083.185
#Sta/Elev= 30
    10.1 1135.12    40.2 1120.45    70.4 1108.67    80.5 1105.09    90.5 1104.58
   130.8 1091.67   150.9  1087.2   201.2 1079.65   221.3 1077.41   251.5 1069.04
   321.2 1045.22     331 1042.48   340.7 1042.81   350.4  1039.4   360.1 1037.34
   408.4 1034.22   418.4 1033.09   428.4 1033.54   437.9 1036.27   447.6 1036.74
     467 1049.72   496.5 1067.23   526.8 1087.72     547 1099.54   567.1 1104.62
   587.3 1114.67   647.8 1147.92     668 1153.83   688.2 1165.83   718.5 1180.29
#Mann= 3 , 0 , 0
       0     .06       0   408.4    .045       0   428.4     .06       0
Bank Sta=408.4,428.4
XS Rating Curve= 0 ,0
Exp/Cntr=0.3,0.1

Type RM Length L Ch R = 1 ,29459.4 ,241.4,239.3,237.3
XS GIS Cut Line= 4
     1646221.339      263453.986     1646237.069       263702.52
     1646215.047      263847.236     1646260.664      264100.488
#Sta/Elev= 30
      10 1148.53    19.9 1146.91    69.7 1116.35    99.6 1099.09   109.6 1094.06
   119.5 1093.73   139.5 1083.09   179.3 1059.86   219.1 1038.14   229.1 1037.38
   239.1 1035.19     249 1034.13   278.3  1031.8   326.9 1029.19   327.1 1029.18
   336.9 1029.18   346.9 1030.19   356.4 1034.18   366.1  1041.9   375.9 1048.78
   425.1 1078.13     435 1078.34   454.8 1089.47   484.5  1107.5   524.1 1129.71
   543.9 1135.11   603.3  1169.9   632.9 1188.65   642.8 1194.46   652.7 1194.89
#Mann= 3 , 0 , 0
       0     .06       0   326.9    .045       0   346.9     .06       0
Bank Sta=326.9,346.9
XS Rating Curve= 0 ,0
Exp/Cntr=0.3,0.1

Type RM Length L Ch R = 1 ,29220   ,342.7,353,363.3
XS GIS Cut Line= 4
     1646021.569      263464.997     1645993.255      263680.498
     1645980.671       263859.82     1646031.007      264131.948
#Sta/Elev= 30
     9.9 1143.21      79 1105.57    88.9 1105.18   118.6 1088.58   177.8 1053.36
   187.7 1051.73   197.6 1047.47   207.5 1041.45   217.4 1036.95   227.3    1035
   277.3 1029.89   297.2 1028.71  330.78 1024.67   347.2 1023.62  350.13 1024.45
   357.2 1026.59   377.1 1040.96   387.1 1045.08   397.1 1047.06   426.8 1064.76
   466.3 1091.83   476.2 1098.26   486.1 1103.78     496 1108.04   505.8 1108.56
   515.7  1112.4   594.8 1157.63   614.6 1163.43   644.2 1181.29   673.9 1197.78
#Mann= 3 , 0 , 0
     9.9     .06       0  330.78    .045       0  350.13     .06       0
Bank Sta=330.78,350.13
XS Rating Curve= 0 ,0
Exp/Cntr=0.3,0.1

Type RM Length L Ch R = 1 ,28867   ,278,262.4,246.8
XS GIS Cut Line= 4
     1645747.867      263436.683     1645692.812      263666.341
     1645626.746      263793.754     1645510.345      264139.813
#Sta/Elev= 30
     9.8 1146.78    68.9 1105.45    78.7 1099.47    88.6 1098.67   118.1 1079.52
   177.1 1045.89   196.8 1040.32   226.3 1024.06   236.2 1021.77   245.7 1021.12
   312.7  1019.2   331.4 1017.75   341.4 1017.61   351.4 1019.37   370.1 1024.94
   419.2 1029.47   438.9 1031.85   448.8  1034.2   458.6  1039.7   488.2 1061.73
   498.1 1067.51     508 1068.62   557.3  1085.4     577  1091.2   606.6 1098.73
   616.5 1099.38   665.9 1113.83   715.2 1135.24   725.1 1137.84   744.8 1149.59
#Mann= 3 , 0 , 0
       0     .06       0   331.4    .045       0   351.4     .06       0
Bank Sta=331.4,351.4
XS Rating Curve= 0 ,0
Exp/Cntr=0.3,0.1

Type RM Length L Ch R = 1 ,28604.6 ,188.6,177.3,166.1
XS GIS Cut Line= 4
     1645447.425      263398.931     1645445.852       263592.41
     1645460.009      263716.677     1645489.896      264119.364
#Sta/Elev= 30
     9.7 1142.89    19.3 1137.48    38.7 1129.18    77.4 1114.18    96.7 1110.24
   106.4 1104.97   125.8  1091.1   183.8 1043.63   193.5 1043.47   203.1  1036.7
   212.7 1028.32   222.3 1018.97   231.6 1013.47   241.6 1012.69   251.6 1013.83
     369  1020.6   399.3 1023.86   409.4  1024.1   439.7 1028.78   449.8 1031.15
     470 1038.53   500.3 1052.59   510.4 1053.03   601.2 1098.13   611.3 1098.25
   641.6  1113.5   651.7 1117.47     682 1127.26   712.3 1138.24   722.4 1139.66
#Mann= 3 , 0 , 0
       0     .08       0   231.6    .045       0   251.6     .06       0
Bank Sta=231.6,251.6
XS Rating Curve= 0 ,0
Exp/Cntr=0.3,0.1

Type RM Length L Ch R = 1 ,28427.3 ,145.9,138.5,131.1
XS GIS Cut Line= 4
     1645398.662      263431.964     1645260.238      263660.049
     1645340.461      263787.462     1645461.582      264105.207
#Sta/Elev= 30
     9.9 1121.74    19.8  1118.1    39.5  1109.4    49.4 1106.85    59.3 1105.74
   118.6  1088.2   158.1 1070.55     168 1067.97   177.9 1067.39   217.4  1049.5
   237.2  1041.9   266.8 1032.64   286.9 1029.45     307  1020.4   327.1 1009.15
   337.1 1006.87   347.1 1007.89   357.1  1010.8   367.2 1012.82   507.4 1024.15
   537.4 1028.98   567.4 1043.93   637.4 1080.59   647.4 1084.48   657.4 1086.78
   697.4 1109.71   707.4 1113.23   727.4 1123.71   747.4 1132.99   757.4 1135.11
#Mann= 3 , 0 , 0
       0     .08       0   327.1    .045       0   347.1     .06       0
Bank Sta=327.1,347.1
XS Rating Curve= 0 ,0
Exp/Cntr=0.3,0.1

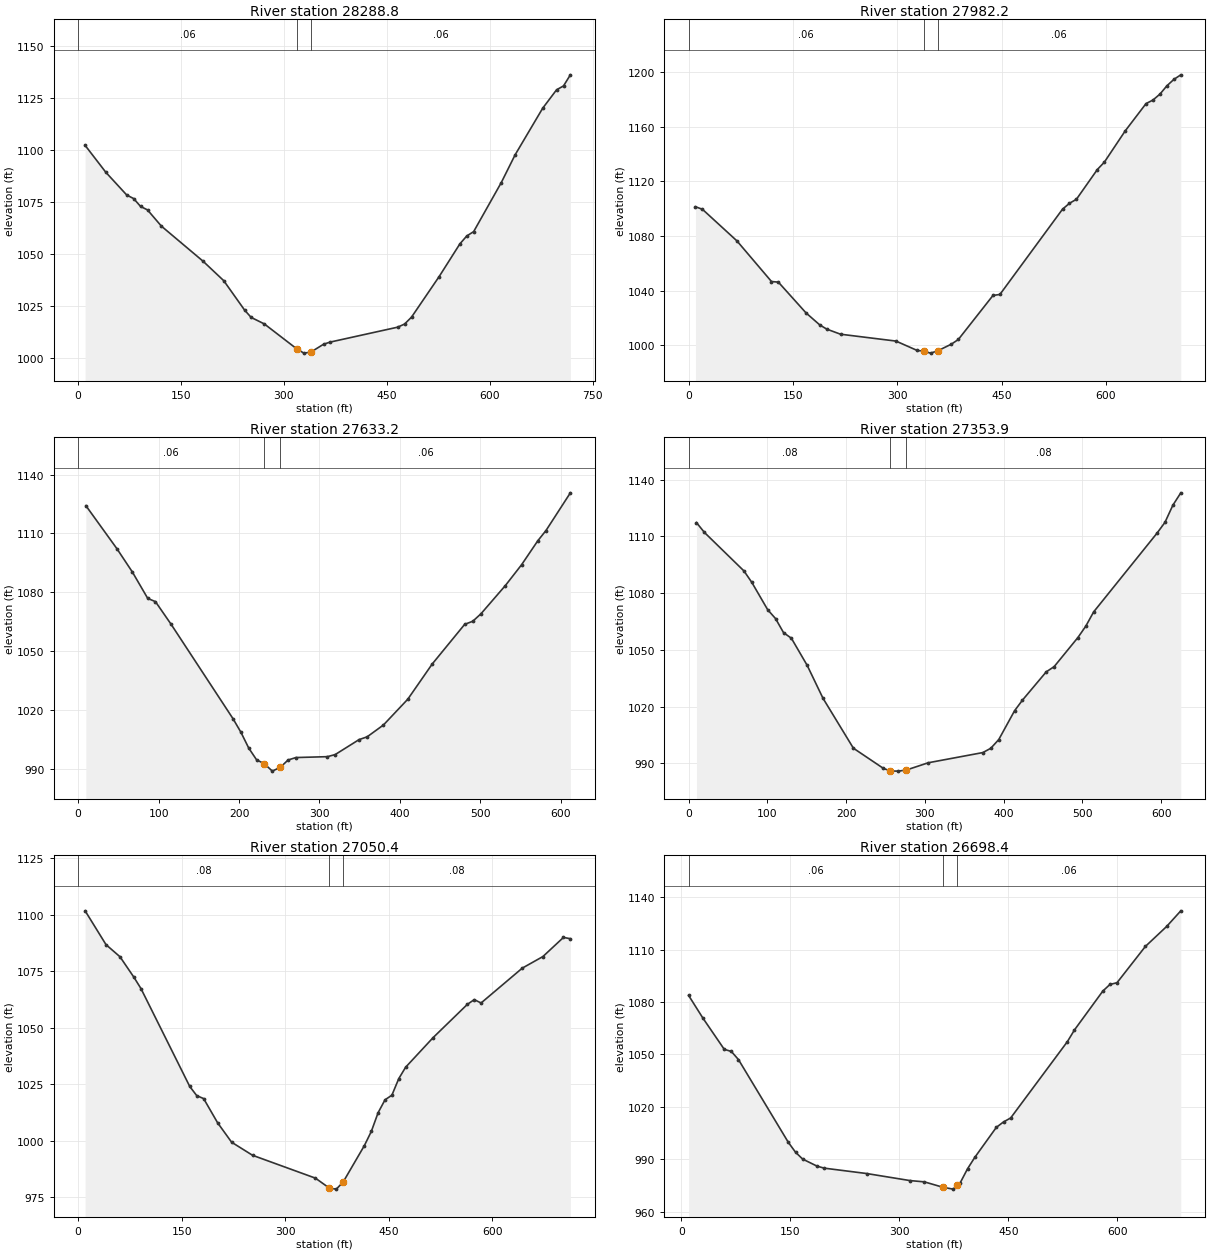
Type RM Length L Ch R = 1 ,28288.8 ,285.5,306.5,327.6
XS GIS Cut Line= 4
     1644947.212      263584.545      1645124.96       263749.71
     1645255.519      263862.966     1645412.819      264120.937
#Sta/Elev= 30
    10.1 1102.23    40.4 1089.23    70.8 1078.32    80.9  1076.6      91 1072.81
   101.1 1071.15   121.3 1063.35     182 1046.48   212.3 1037.06   242.6 1022.95
   252.2  1019.4   271.4 1016.27   319.1 1004.16   329.1 1002.21   339.1 1002.68
   357.9 1006.51   367.5 1007.53   465.8  1014.7   475.9 1016.21     486 1019.53
   526.3 1039.07   556.5 1054.79   566.5 1058.58   576.6  1060.7   616.9 1084.32
   637.1 1097.69   677.3 1120.12   697.5 1128.96   707.6 1130.82   717.6 1136.16
#Mann= 3 , 0 , 0
       0     .06       0   319.1    .045       0   339.1     .06       0
Bank Sta=319.1,339.1
XS Rating Curve= 0 ,0
Exp/Cntr=0.3,0.1

Type RM Length L Ch R = 1 ,27982.2 ,360.2,349,337.8
XS GIS Cut Line= 4
     1644900.022      263617.578     1644947.212      263861.393
     1644951.931      264040.714     1645040.018      264306.551
#Sta/Elev= 30
     9.9 1101.51    19.9 1099.66    69.5 1076.53   119.2 1046.77   129.1 1046.32
   168.9 1023.78   188.7 1014.96   198.7 1011.92   218.5 1008.19   298.2 1003.16
   328.1  996.43     338  995.67     348  994.34     358  995.96   377.9 1000.91
   387.9 1004.33   437.7 1036.56   447.7 1037.31   537.7 1099.72   547.7 1104.04
   557.7 1106.98   587.8 1128.77   597.8 1134.12   627.8 1157.01   657.8 1177.04
   667.8 1179.65   677.8 1183.98   687.8 1190.06   697.8 1194.74   707.8  1198.1
#Mann= 3 , 0 , 0
       0     .06       0     338    .045       0     358     .06       0
Bank Sta=338,358
XS Rating Curve= 0 ,0
Exp/Cntr=0.3,0.1

Type RM Length L Ch R = 1 ,27633.2 ,285.7,279.4,273.1
XS GIS Cut Line= 4
     1644476.885      263829.933     1644580.703      263968.356
     1644656.207      264116.218      1644815.08      264338.011
#Sta/Elev= 30
     9.6 1124.15    48.1 1102.29    67.3 1090.44    86.5 1076.95    96.1 1075.29
   115.4 1063.86   192.6 1015.65   202.3 1008.83   212.1 1000.72   221.9  994.73
   231.4  992.81   241.4  989.02   251.4  990.99   260.9  994.67   270.7  995.93
   309.8  996.38   319.5  997.44   349.2 1005.06   359.3 1006.49   379.5  1012.5
   409.8 1025.64   440.1 1043.52   480.5 1063.73   490.6 1065.32   500.7 1069.09
     531 1083.44   551.2 1094.05   571.5 1106.33   581.6  1111.5   611.9 1130.68
#Mann= 3 , 0 , 0
       0     .06       0   231.4    .045       0   251.4     .06       0
Bank Sta=231.4,251.4
XS Rating Curve= 0 ,0
Exp/Cntr=0.3,0.1

Type RM Length L Ch R = 1 ,27353.9 ,302.1,303.4,304.8
XS GIS Cut Line= 4
     1644217.341      263991.951     1644335.316      264128.802
     1644429.696      264235.766     1644667.218       264421.38
#Sta/Elev= 30
      10 1117.28    20.1 1112.07    70.3  1091.7    80.3 1085.63   100.4  1071.2
   110.4 1066.51   120.5  1059.1   130.5 1056.11   150.6 1041.73   170.6 1024.38
   209.2  997.97   247.3   987.3   256.3  985.93   266.3  985.85   276.3  986.42
   304.3  990.28   373.6  995.67   383.6  997.94   393.7 1002.53   413.8 1017.78
   423.8 1023.39     454 1038.35     464 1041.09   494.2  1056.5   504.2 1062.51
   514.2 1070.06   594.6 1111.68   604.7  1117.4   614.7 1126.45   624.8 1133.01
#Mann= 3 , 0 , 0
       0     .08       0   256.3    .045       0   276.3     .08       0
Bank Sta=256.3,276.3
XS Rating Curve= 0 ,0
Exp/Cntr=0.3,0.1

Type RM Length L Ch R = 1 ,27050.4 ,344.6,352,359.3
XS GIS Cut Line= 4
     1644044.311      264108.353     1644149.702      264338.011
     1644258.239      264471.716     1644412.393       264715.53
#Sta/Elev= 30
    10.1 1101.66    40.4 1086.69    60.6 1081.35    80.9 1072.24      91 1067.29
   161.7 1023.98   171.8 1019.93   181.9 1018.58   202.1  1007.9   222.4   999.3
   252.7  993.52   343.9   983.4   364.2  978.97   374.2  978.54   384.2  981.75
   414.8  997.78   424.9 1004.07   434.8 1012.39   444.8 1018.07   454.7 1020.09
   464.7 1027.42   474.6 1032.46   514.4 1045.55   564.2 1060.31   574.1 1062.37
     584 1060.89   643.7 1076.31   673.6 1081.43   703.4  1089.9   713.4 1089.32
#Mann= 3 , 0 , 0
       0     .08       0   364.2    .045       0   384.2     .08       0
Bank Sta=364.2,384.2
XS Rating Curve= 0 ,0
Exp/Cntr=0.3,0.1

Type RM Length L Ch R = 1 ,26698.4 ,225.8,230.3,234.8
XS GIS Cut Line= 4
     1643736.004      264271.945     1643876.001      264496.884
     1643943.639      264662.048     1644105.658      264844.516
#Sta/Elev= 30
     9.8  1083.8    29.4 1070.87    58.9 1052.93    68.7  1051.7    78.5 1047.04
   147.2  999.62     157  994.05   166.8  990.12   186.4  986.12   196.3  984.93
   255.1  981.83   314.5  977.81   334.4  977.07  360.15  973.95     374  972.91
  379.94  975.09   383.9  976.67   393.8  984.54   403.8  991.09   433.5 1008.28
   443.4 1011.38   453.2 1013.64   531.3 1057.35     541 1064.01   580.1 1086.29
   589.8 1090.04   599.6 1091.06   638.6  1111.8   667.9 1123.25   687.4  1132.2
#Mann= 3 , 0 , 0
     9.8     .06       0  360.15    .045       0  379.94     .06       0
Bank Sta=360.15,379.94
XS Rating Curve= 0 ,0
Exp/Cntr=0.3,0.1