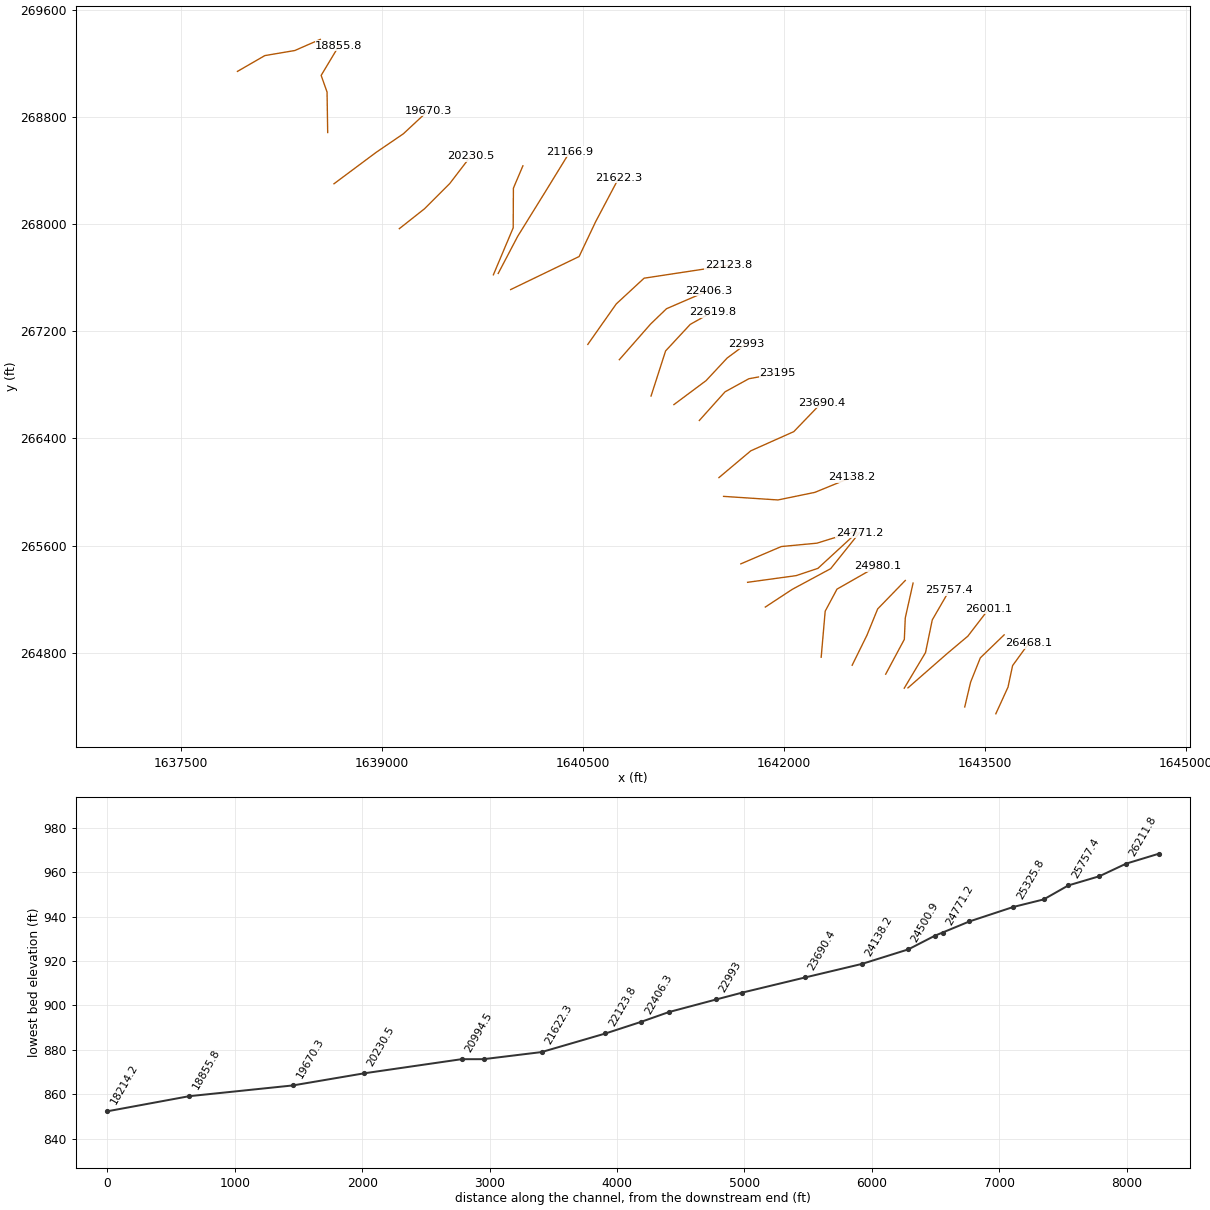
HEC-RAS study dmsfrk.prj: dmsfrk

--- dmsfrk.g01 (geometry) --- (continued)

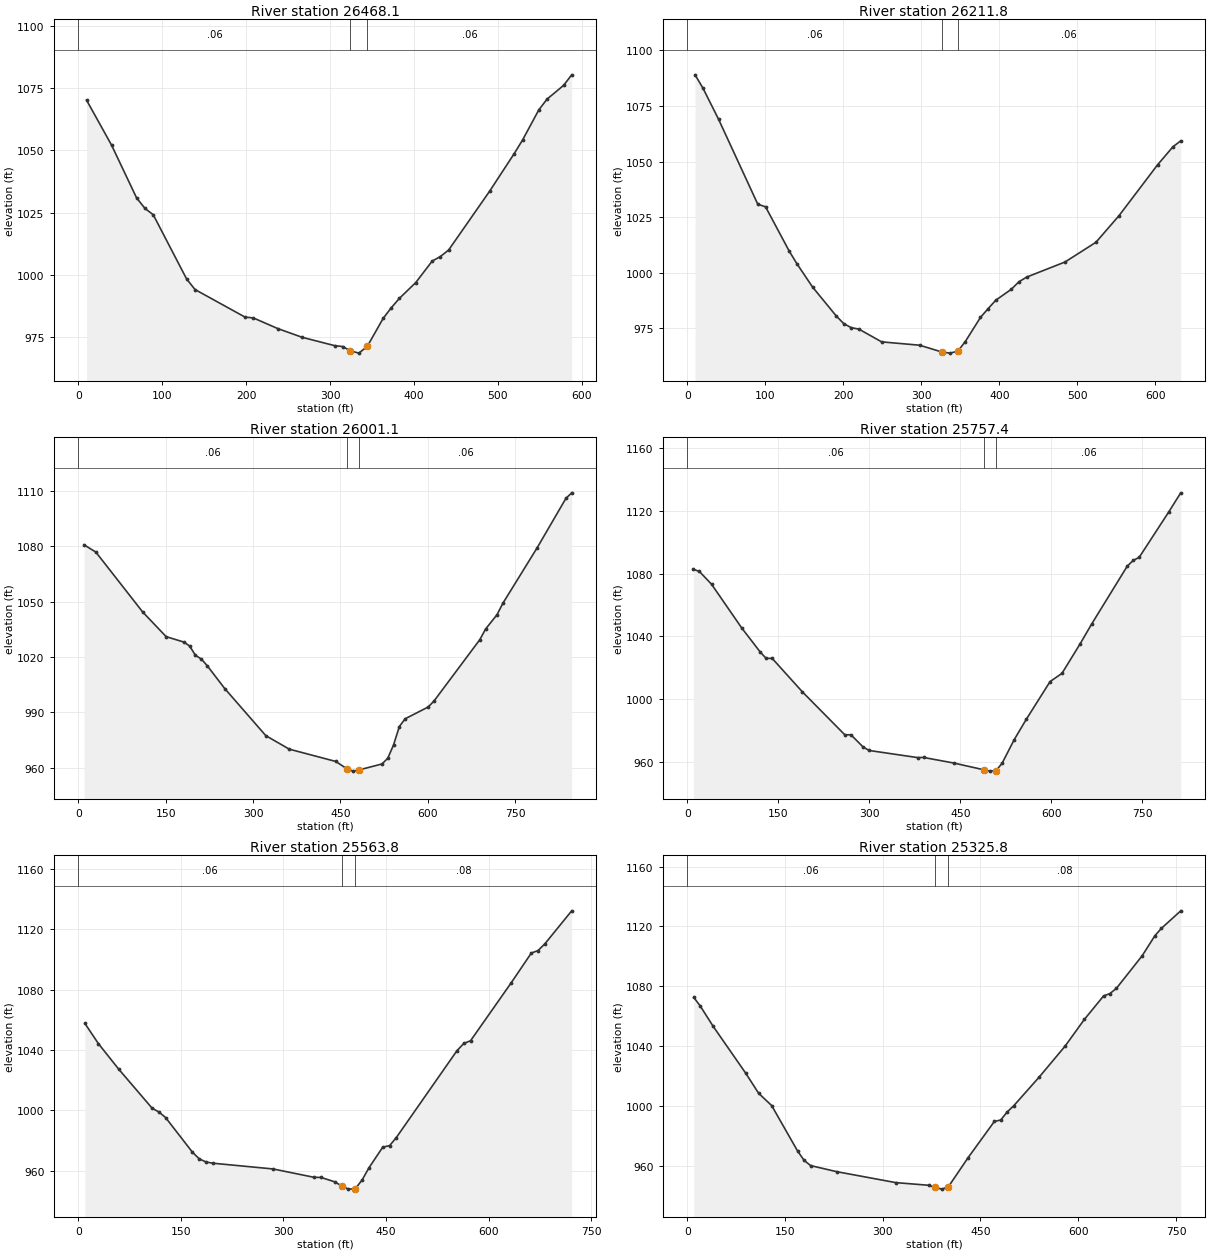
Type RM Length L Ch R = 1 ,26468.1 ,260.5,256.3,252
XS GIS Cut Line= 4
     1643579.611      264345.516      1643670.47      264544.269
     1643704.542      264704.691     1643825.213      264870.791
#Sta/Elev= 30
     9.9 1070.31    39.7 1052.16    69.5 1030.91    79.5 1026.64    89.4 1024.08
   129.1  998.22   139.1  993.96   198.7  982.84   208.6  982.51   237.8   978.2
   266.8  974.69   305.4  971.34     315  970.97   324.3  969.25   334.3  968.32
   344.3  971.03   363.2  982.32   372.9   986.6   382.5  990.38   402.1  996.78
   421.6 1005.41   431.4 1007.26   441.2 1009.88   490.1 1033.62   519.4 1048.78
   529.2 1054.18   548.7 1066.41   558.5 1070.72   578.1 1076.23   587.8 1080.49
#Mann= 3 , 0 , 0
       0     .06       0   324.3    .045       0   344.3     .06       0
Bank Sta=324.3,344.3
XS Rating Curve= 0 ,0
Exp/Cntr=0.3,0.1

Type RM Length L Ch R = 1 ,26211.8 ,223.1,210.7,198.3
XS GIS Cut Line= 4
     1643347.474      264396.212     1643391.517      264581.825
     1643463.875       264762.72     1643641.624      264934.177
#Sta/Elev= 30
      10    1089    20.1 1083.03    40.2 1068.98    90.4 1030.83   100.4 1029.64
   130.5 1009.87   140.6 1004.03   160.6  993.59   190.8  980.66   200.5  977.15
   210.3  975.29     220  974.67   249.2  968.92   297.9  967.42   326.9  964.31
   336.9  963.86   346.9  964.76   356.4  969.05   375.9  979.93   385.6  983.83
   395.5  987.66   415.2  992.51   425.1  995.92     435  998.03   484.4 1004.86
   523.9 1013.71   553.5 1025.68   602.9 1048.54   622.7 1056.69   632.6 1059.31
#Mann= 3 , 0 , 0
       0     .06       0   326.9    .045       0   346.9     .06       0
Bank Sta=326.9,346.9
XS Rating Curve= 0 ,0
Exp/Cntr=0.3,0.1

Type RM Length L Ch R = 1 ,26001.1 ,226.9,243.8,260.7
XS GIS Cut Line= 4
     1642923.726       264538.59     1643219.017      264796.969
     1643370.921      264924.739     1643527.084      265127.751
#Sta/Elev= 30
    10.1 1080.81    30.2 1076.91   110.7 1044.41   150.9 1031.07   181.1 1028.15
   191.2    1026   201.2 1020.94   211.3 1018.95   221.3 1015.36   251.5 1002.93
   321.9  977.43   362.2  970.09     442  963.43   461.8  959.31   471.8  958.18
   481.8  958.82   521.4  962.06   531.3  965.16   541.2  972.35   551.2  982.35
   561.1  986.54   600.7  992.94   610.6  996.15   689.4 1029.49   699.2 1035.19
   718.9    1043   728.8 1049.12   787.9 1079.34   837.1 1106.02     847 1109.01
#Mann= 3 , 0 , 0
       0     .06       0   461.8    .045       0   481.8     .06       0
Bank Sta=461.8,481.8
XS Rating Curve= 0 ,0
Exp/Cntr=0.3,0.1

Type RM Length L Ch R = 1 ,25757.4 ,189.5,193.5,197.5
XS GIS Cut Line= 4
     1642896.023      264536.209     1643054.896      264802.045
     1643105.232      265045.859     1643232.645      265266.079
#Sta/Elev= 30
      10 1082.87      20 1081.46      40 1073.32    89.9 1045.32   119.9 1030.23
   129.9 1026.01   139.9    1026   189.8 1004.59   259.7  977.19   269.7  977.25
   289.7  969.46   299.7  967.22   379.4  962.69   389.4  962.77   439.2   959.2
   488.9  954.88   498.9  954.04   508.9  954.39   518.8  959.08   538.7  974.13
   558.6   987.1   597.8 1011.19   617.4 1016.43   646.7 1034.87   666.3  1047.9
     725 1084.87   734.8  1088.5   744.6 1090.45   793.5 1119.53   813.1 1131.64
#Mann= 3 , 0 , 0
       0     .06       0   488.9    .045       0   508.9     .06       0
Bank Sta=488.9,508.9
XS Rating Curve= 0 ,0
Exp/Cntr=0.3,0.1

Type RM Length L Ch R = 1 ,25563.8 ,246.6,238.1,229.5
XS GIS Cut Line= 4
     1642757.626      264640.806     1642896.753      264900.604
     1642903.851      265061.026     1642962.057      265320.825
#Sta/Elev= 30
     9.8 1057.56    29.5  1044.2    58.9 1027.42   108.1 1001.36   117.9   998.9
   127.7  995.22     167  972.21   176.8  967.86   186.6  965.78   196.5  964.94
   284.9  961.11   344.9  955.56   354.9   955.5     375  952.59   385.1  949.88
   395.1  947.74   405.1  947.97   415.1  953.85   425.2  961.97   445.2  975.53
   455.3   976.6   465.1  981.94   553.9 1039.61   563.8 1044.33   573.6 1046.09
   632.8 1084.36   662.4 1104.19   672.2 1105.89   682.1 1110.26   721.5 1132.22
#Mann= 3 , 0 , 0
       0     .06       0   385.1    .045       0   405.1     .08       0
Bank Sta=385.1,405.1
XS Rating Curve= 0 ,0
Exp/Cntr=0.3,0.1

Type RM Length L Ch R = 1 ,25325.8 ,348.3,345.7,343.1
XS GIS Cut Line= 4
     1642507.493      264707.665     1642617.603      264931.031
     1642697.826      265127.655     1642903.888       265340.01
#Sta/Elev= 30
      10 1072.55    19.9 1066.84    39.8 1053.18    89.7 1021.89   109.6 1008.42
   129.5 1000.25   169.3  969.85   179.3   963.6   189.3  960.09   229.1  956.05
   319.8  948.72   370.4  946.93   380.6  945.44   390.6  944.35   400.6  945.85
   431.1  965.46   471.3  989.62   481.1  990.57     491  995.98   500.8  999.99
   540.3 1019.39   579.8 1039.95   609.3 1057.78   638.9 1073.53   648.8 1075.14
   658.7 1078.68   698.1 1100.39   717.8  1113.9   727.7 1118.75   757.3 1130.44
#Mann= 3 , 0 , 0
       0     .06       0   380.6    .045       0   400.6     .08       0
Bank Sta=380.6,400.6
XS Rating Curve= 0 ,0
Exp/Cntr=0.3,0.1

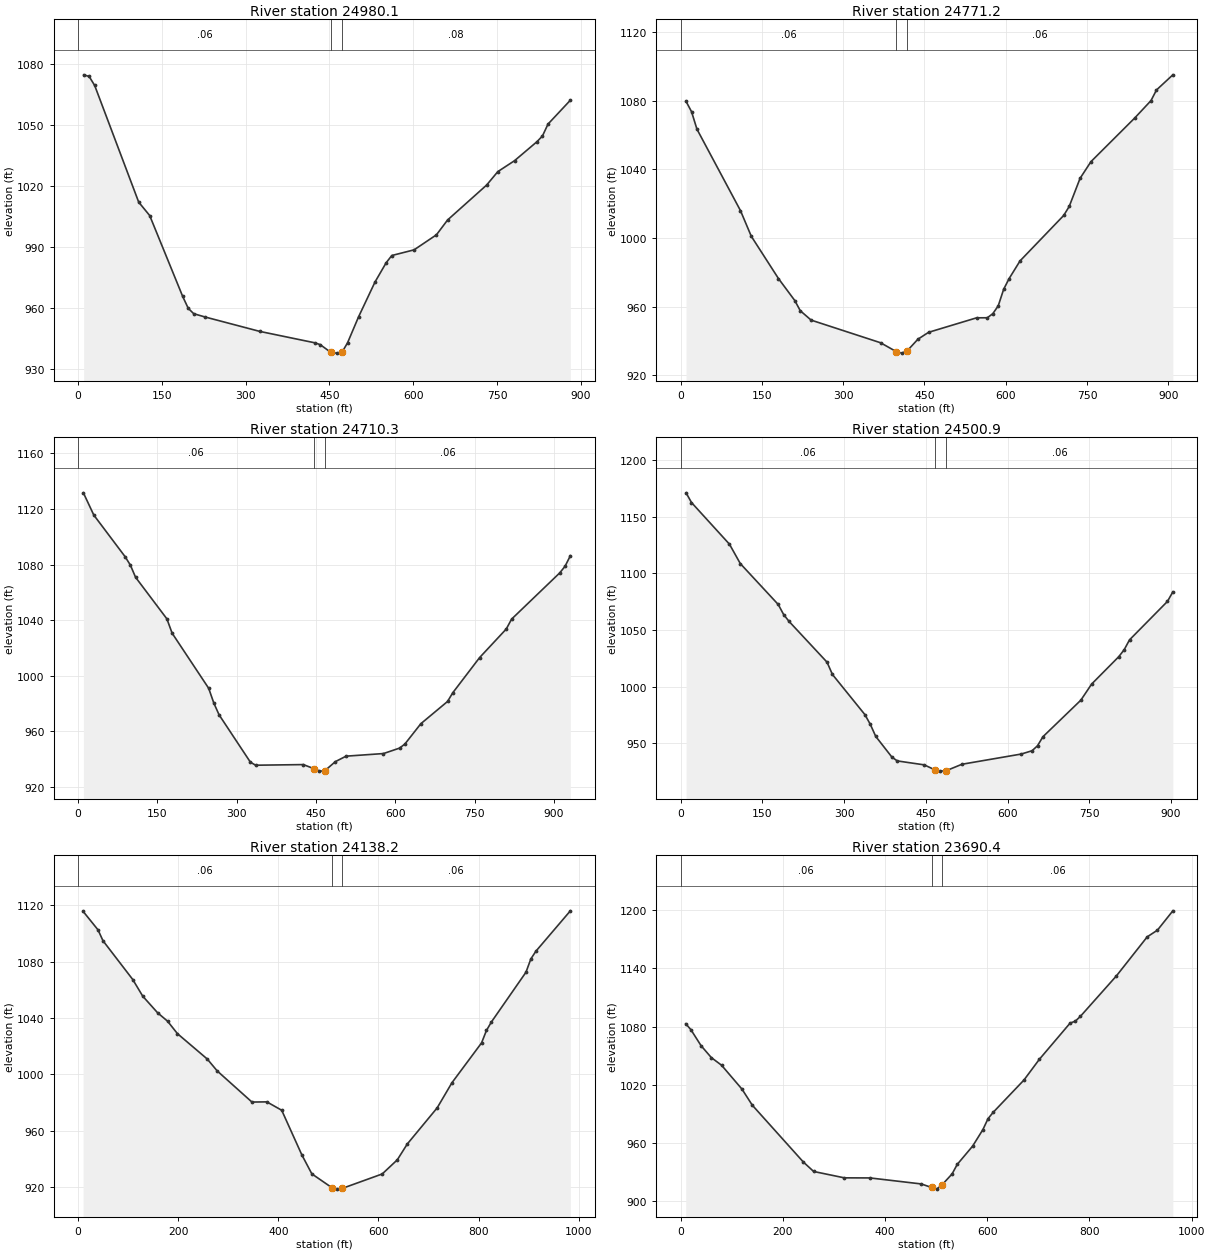
Type RM Length L Ch R = 1 ,24980.1 ,223.6,208.9,194.2
XS GIS Cut Line= 4
      1642276.36      264767.156     1642306.173      265110.715
     1642394.192      265275.396        1642698.      265448.595
#Sta/Elev= 30
     9.9 1074.91    19.7  1074.1    29.6 1069.66   108.4  1012.2   128.1 1005.58
   187.2  965.73   197.1  959.89   206.9  957.24   226.6  955.66   325.1  948.52
   423.5  942.91   433.3  942.01   452.8  938.12   462.8  937.81   472.8   938.4
   482.4  942.92   502.1   955.7   531.6  972.89   551.6  982.38   561.6   985.9
   601.5  988.69   641.5  996.09   661.5 1003.41   731.4 1020.61   751.4 1027.22
   781.4 1032.62   821.3 1041.92   831.3 1044.77   841.3 1050.65   881.3  1062.4
#Mann= 3 , 0 , 0
       0     .06       0   452.8    .045       0   472.8     .08       0
Bank Sta=452.8,472.8
XS Rating Curve= 0 ,0
Exp/Cntr=0.3,0.1

Type RM Length L Ch R = 1 ,24771.2 ,65.2,60.8,56.5
XS GIS Cut Line= 4
     1641859.418      265141.812     1642060.762      265273.944
     1642347.047      265428.098     1642560.975      265695.507
#Sta/Elev= 30
      10 1079.69    20.1 1073.69    30.1 1063.48   110.4 1015.99   130.4    1001
   180.6  976.33   210.7  963.51   220.8  957.58   240.8  952.11   368.9  938.91
   398.3  933.68   408.3  932.85   418.3  934.25   437.9  940.97   457.6  944.99
   546.3  953.45     566  953.48   576.1  955.85   586.1  960.41   596.2  970.13
   606.3  976.37   626.4  986.65     707 1013.17   717.1 1018.39   737.2 1034.82
   757.3 1044.55   837.9 1069.95   868.1 1080.15   878.2 1086.34   908.4 1095.18
#Mann= 3 , 0 , 0
       0     .06       0   398.3    .045       0   418.3     .06       0
Bank Sta=398.3,418.3
XS Rating Curve= 0 ,0
Exp/Cntr=0.3,0.1

Type RM Length L Ch R = 1 ,24710.3 ,215.1,209.4,203.8
XS GIS Cut Line= 4
     1641727.264      265326.409     1642089.057      265376.113
     1642252.038       265430.44     1642541.837      265697.036
#Sta/Elev= 30
     9.9 1131.56    29.6 1115.57    88.8 1085.63    98.7 1079.61   108.6 1070.82
   167.8 1040.92   177.7 1030.63   246.8  991.02   256.6  980.34   266.5  971.91
   325.7  937.87   335.6  935.67   425.8  936.12   446.1  933.17   456.1  931.42
   466.1  931.59   486.5  938.27   506.7  942.18   577.4  944.06   607.7  947.96
   617.8  950.88   648.1  965.54   698.5   981.5   708.6  987.86   759.1 1013.04
   809.6 1033.64   819.7 1040.75   910.6 1073.94   920.7 1078.71   930.8 1086.34
#Mann= 3 , 0 , 0
       0     .06       0   446.1    .045       0   466.1     .06       0
Bank Sta=446.1,466.1
XS Rating Curve= 0 ,0
Exp/Cntr=0.3,0.1

Type RM Length L Ch R = 1 ,24500.9 ,360,362.7,365.4
XS GIS Cut Line= 4
      1641676.95      265464.277     1641978.966      265593.263
     1642244.803      265618.431     1642538.953      265709.664
#Sta/Elev= 30
      10 1171.27    19.9 1162.71    89.6 1125.86   109.5 1108.72   179.1 1072.57
   189.1 1063.63     199 1057.59   268.7 1021.55   278.6  1010.7   338.3  975.13
   348.2  966.52   358.1  955.93   387.7  937.67   397.6  934.27   447.1  930.78
   466.8  926.34   476.8  925.24   486.8  925.49   516.3  931.31   625.2  940.35
   645.1  943.28     655  947.67     665  955.67   734.5  987.95   754.4 1002.24
   804.1 1026.39     814 1032.51   823.9  1041.3   893.5 1075.28   903.4 1083.72
#Mann= 3 , 0 , 0
       0     .06       0   466.8    .045       0   486.8     .06       0
Bank Sta=466.8,486.8
XS Rating Curve= 0 ,0
Exp/Cntr=0.3,0.1

Type RM Length L Ch R = 1 ,24138.2 ,442.3,447.8,453.2
XS GIS Cut Line= 4
     1641547.965      265967.636     1641953.798      265940.895
     1642229.072      265997.523     1642502.774      266109.205
#Sta/Elev= 30
     9.9 1115.63    39.7 1102.51    49.6 1094.81   109.1 1067.31     129 1055.53
   158.7 1043.75   178.6 1037.79   198.4 1028.93   257.9 1010.97   277.8 1002.52
   347.2  980.45     377  980.58   406.7  974.63   446.9  943.01   466.9  929.54
   507.1  919.72   517.1  918.72   527.1  919.17   607.5  929.47   637.6  939.47
   657.6  950.72   717.3  976.33   746.9  994.19     806 1022.39   815.8 1031.23
   825.7 1037.25   894.7 1072.48   904.5 1081.93   914.4 1087.32   983.4 1116.01
#Mann= 3 , 0 , 0
       0     .06       0   507.1    .045       0   527.1     .06       0
Bank Sta=507.1,527.1
XS Rating Curve= 0 ,0
Exp/Cntr=0.3,0.1

Type RM Length L Ch R = 1 ,23690.4 ,493.3,495.4,497.5
XS GIS Cut Line= 4
     1641513.359      266107.633     1641750.881      266307.403
     1642071.773      266450.546     1642280.981       266667.62
#Sta/Elev= 30
      10 1082.91      20 1076.89      40 1060.33    60.1 1048.06    80.1 1040.21
   120.1 1015.56   140.2  999.07   240.3  940.42   260.3  930.78   320.4  924.22
   370.6  924.13     471  917.93   491.1  914.29   501.1   912.6   511.1  916.78
   531.2  928.25   541.3  938.08   571.4   956.9   591.5  973.93   601.5  985.12
   611.5  991.64   671.8 1024.94   701.9 1046.26   762.2 1083.63   772.3 1085.57
   782.3 1090.56   852.7 1132.18     913 1172.41   933.1 1179.36   963.2 1199.24
#Mann= 3 , 0 , 0
       0     .06       0   491.1    .045       0   511.1     .06       0
Bank Sta=491.1,511.1
XS Rating Curve= 0 ,0
Exp/Cntr=0.3,0.1

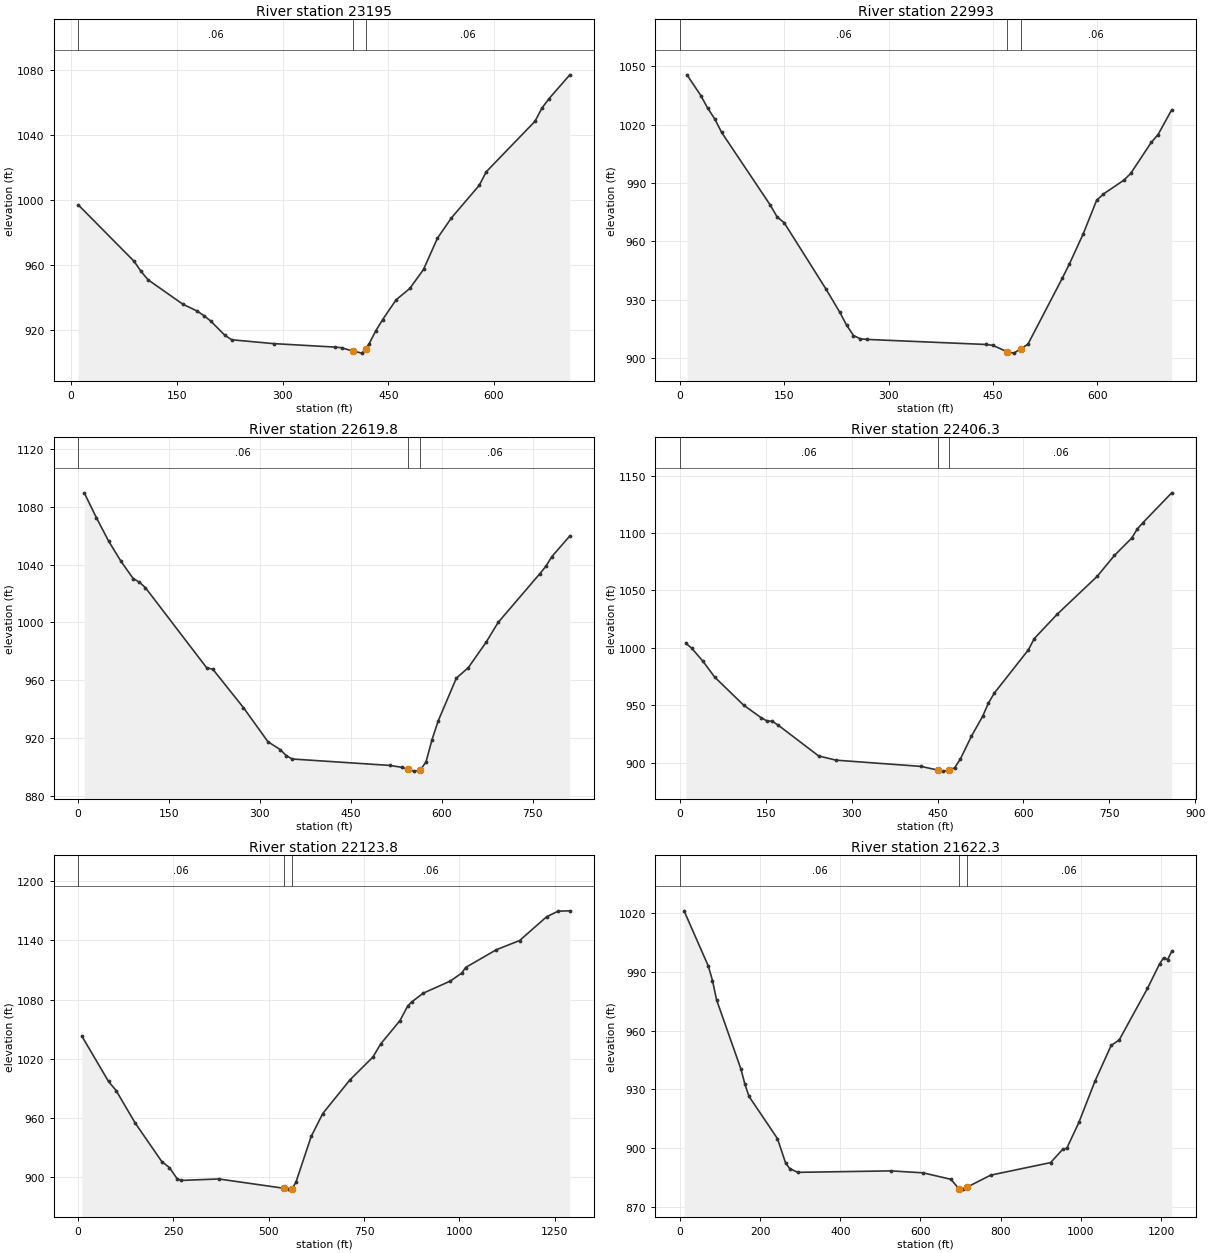
Type RM Length L Ch R = 1 ,23195   ,194,202,210.1
XS GIS Cut Line= 4
      1641367.07      266533.915     1641558.976      266747.842
     1641736.724      266845.368     1641950.652      266884.693
#Sta/Elev= 30
     9.9  997.23    89.2  962.42    99.1  956.21     109  951.01   158.6  935.89
   178.4  931.79   188.3  928.92   198.2  925.46     218  916.82   227.9  913.98
   287.4  911.61   374.3  909.48   383.9  909.07  399.65     907   412.9  905.75
   417.8  908.45   422.6  911.31   432.2  919.42   441.9  926.35   461.2  938.65
   480.5  945.59     500   957.3   519.8  976.62   539.6  989.09   579.1  1009.2
     589 1017.52   658.2 1048.66   668.1 1056.81     678 1062.56   707.6  1077.3
#Mann= 3 , 0 , 0
     9.9     .06       0  399.65    .045       0   417.8     .06       0
Bank Sta=399.65,417.8
XS Rating Curve= 0 ,0
Exp/Cntr=0.3,0.1

Type RM Length L Ch R = 1 ,22993   ,373.2,373.2,373.3
XS GIS Cut Line= 4
     1641177.539       266652.47     1641417.463      266831.348
     1641575.046      267000.288     1641717.012      267105.343
#Sta/Elev= 30
      10  1045.5    29.9 1034.85    39.9 1028.33    49.9 1022.89    59.9 1015.91
   129.7   978.7   139.7  972.54   149.6  969.69   209.5  935.78   229.4  923.86
   239.4  917.11   249.4  911.74   259.4  910.04   269.3  909.73   439.9  907.14
   449.9  906.69   470.1  903.41   480.1   902.7   490.1  904.98   500.2  907.29
   549.9  941.35   559.7  948.36   579.4  963.67     599  981.15   608.8  984.35
   638.2  991.47     648  994.92   677.5 1010.82   687.3 1014.85   706.9 1027.55
#Mann= 3 , 0 , 0
       0     .06       0   470.1    .045       0   490.1     .06       0
Bank Sta=470.1,490.1
XS Rating Curve= 0 ,0
Exp/Cntr=0.3,0.1

Type RM Length L Ch R = 1 ,22619.8 ,214.8,213.5,212.1
XS GIS Cut Line= 4
     1641006.854      266716.382     1641115.391      267053.004
     1641299.431      267251.202     1641463.023      267342.435
#Sta/Elev= 30
    10.1 1089.67    30.3 1072.36    50.5 1056.13    70.7 1042.28    90.9  1030.3
   101.1 1027.84   111.2 1023.95   212.2  968.52   222.3  967.56   272.8     941
   313.3  917.35   333.5  911.96   343.6   907.7   353.7  905.39     514  900.96
     534  899.67     544  898.27     554     897     564  897.44   574.1  903.27
   584.1  918.78   594.1  931.57   624.2  961.35   643.9  968.58   673.4  986.26
   693.2  999.93   762.2 1033.75     772  1038.8   781.9 1045.54   811.5 1059.81
#Mann= 3 , 0 , 0
       0     .06       0     544    .045       0     564     .06       0
Bank Sta=544,564
XS Rating Curve= 0 ,0
Exp/Cntr=0.3,0.1

Type RM Length L Ch R = 1 ,22406.3 ,283,282.5,282
XS GIS Cut Line= 4
     1640770.096      266987.511     1641002.921      267252.988
     1641122.172      267367.981     1641434.499      267502.849
#Sta/Elev= 30
    10.1 1004.02    20.2  999.85    40.4  988.15    60.5  974.59     111  950.19
   141.2  939.37   151.3  936.54   161.4  936.01   171.5  932.72   242.1  905.91
   272.4  902.23   421.3  896.78   450.3  893.55   460.3  892.67   470.3  893.64
   479.8   895.6   489.5  902.96     509  922.93   528.8  940.55   538.8  951.89
   548.8  960.42   608.8  998.41   618.8 1008.06   658.9 1029.26   728.9 1062.34
   758.9 1080.47   788.9 1095.45   798.9 1103.53   808.9 1109.13     859 1135.02
#Mann= 3 , 0 , 0
       0     .06       0   450.3    .045       0   470.3     .06       0
Bank Sta=450.3,470.3
XS Rating Curve= 0 ,0
Exp/Cntr=0.3,0.1

Type RM Length L Ch R = 1 ,22123.8 ,491.9,501.5,511.1
XS GIS Cut Line= 4
     1640534.955      267101.767     1640747.309      267403.782
     1640954.945      267595.688     1641585.717      267691.641
#Sta/Elev= 30
      10 1042.72    79.8  996.76    99.8  987.48   149.7  954.55   219.5   915.4
   239.5   909.3   259.4  898.15   269.4   896.2   369.2  897.72     541  888.19
     551  887.39     561   887.7   571.2  894.14   611.5  940.89   641.8  964.18
   712.7  998.16   773.5 1021.56   793.7 1034.82   844.4 1058.57   864.6 1073.31
   874.7 1077.37   905.1 1086.39     976 1098.65  1006.4 1106.83  1016.5  1112.5
  1097.5 1130.63  1158.3 1139.91  1229.2 1164.08  1259.6 1169.78    1290 1170.09
#Mann= 3 , 0 , 0
       0     .06       0     541    .045       0     561     .06       0
Bank Sta=541,561
XS Rating Curve= 0 ,0
Exp/Cntr=0.3,0.1

Type RM Length L Ch R = 1 ,21622.3 ,458.2,455.4,452.6
XS GIS Cut Line= 4
     1639959.238      267510.746     1640470.021      267757.258
     1640593.058      268016.583     1640767.204      268345.946
#Sta/Elev= 30
    10.1 1021.28    70.9  992.87      81  985.66    91.2  975.76   151.9  940.45
     162  932.56   172.2   926.4   243.1  904.86   263.3  892.47   273.5  889.55
   293.7   887.6   526.6  888.35   606.7  887.34     676  884.04   695.7  879.23
   705.7  879.02   715.7  879.97     775  886.16   924.7  892.59   954.9  899.39
     965  899.91   995.2  913.12  1035.4  934.22  1075.7  952.45  1095.9   955.3
  1166.3  981.61  1196.5  994.14  1206.6  997.27  1216.7  996.38  1226.8 1000.55
#Mann= 3 , 0 , 0
       0     .06       0   695.7    .045       0   715.7     .06       0
Bank Sta=695.7,715.7
XS Rating Curve= 0 ,0
Exp/Cntr=0.3,0.1

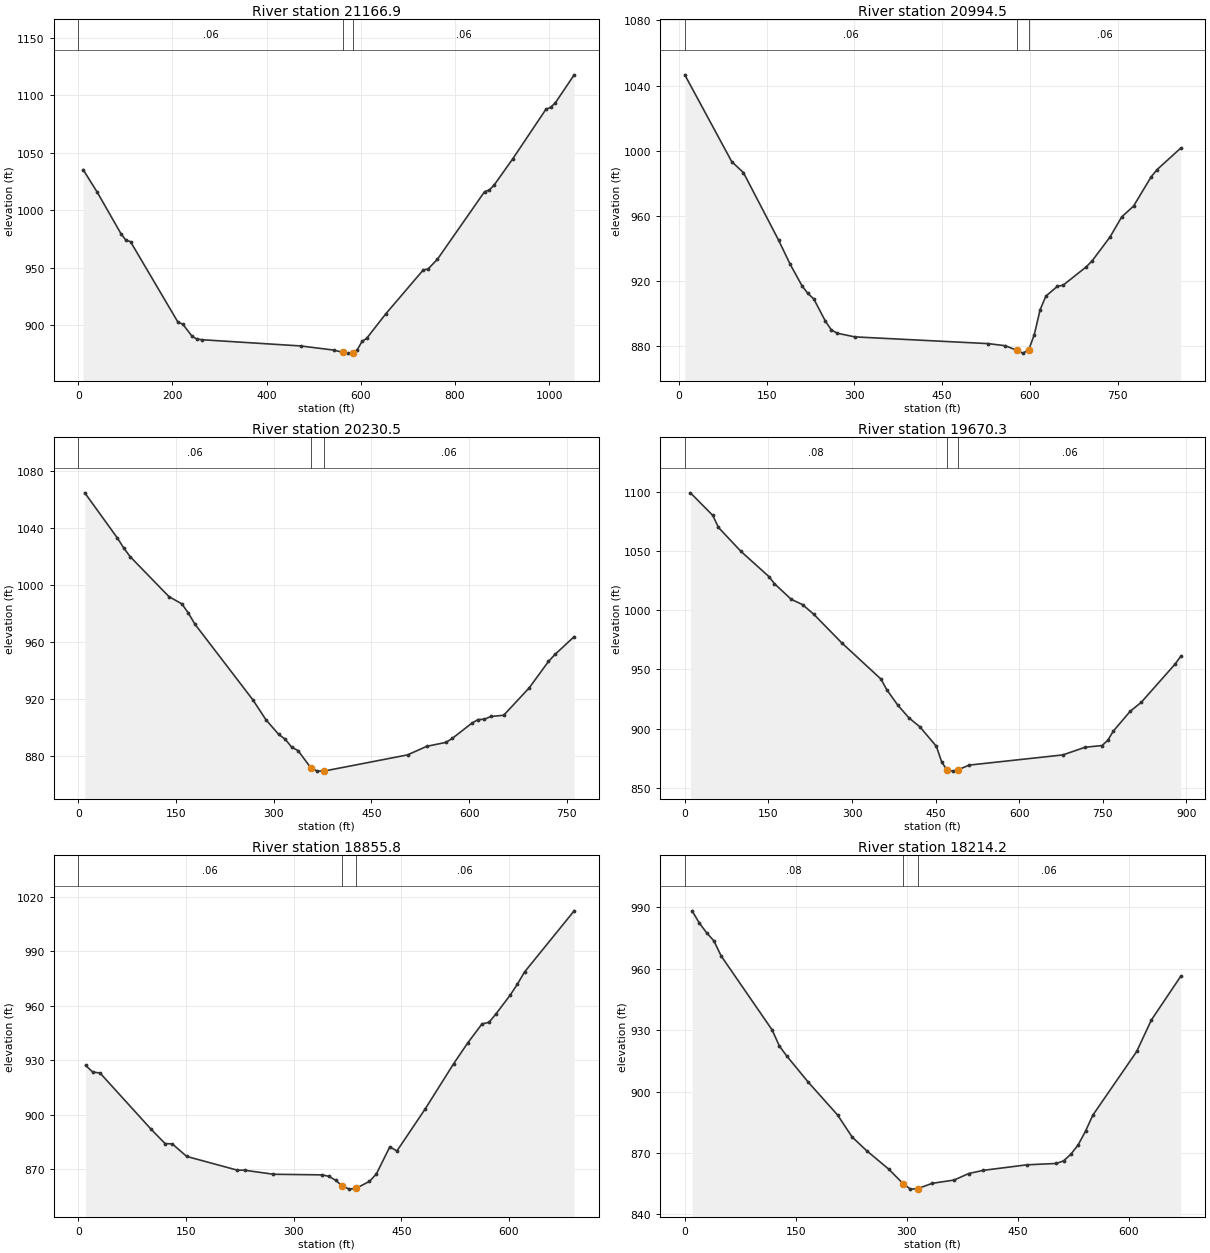
Type RM Length L Ch R = 1 ,21166.9 ,158.5,172.3,186.2
XS GIS Cut Line= 4
     1639866.409      267631.219     1640011.623      267907.947
     1640217.115      268239.474     1640400.687      268538.121
#Sta/Elev= 30
    10.1 1035.37    40.3  1015.6    90.7  979.53   100.8  974.15   110.9  972.66
   211.7  902.68   221.8  901.04   241.9  890.33     252  888.05   262.1   887.5
   472.5  882.06   542.5  878.48   562.5  876.42   572.5  875.83   582.5  876.07
   592.5  878.77   602.6  886.03   612.6  888.78   652.6  909.77   732.6  948.15
   742.6  948.85   762.7  957.44   862.8 1016.15   872.8 1017.61   882.8 1021.72
   922.9 1044.85     993 1087.68    1003 1089.39  1013.1 1093.35  1053.1 1117.72
#Mann= 3 , 0 , 0
       0     .06       0   562.5    .045       0   582.5     .06       0
Bank Sta=562.5,582.5
XS Rating Curve= 0 ,0
Exp/Cntr=0.3,0.1

Type RM Length L Ch R = 1 ,20994.5 ,783.6,764,744.4
XS GIS Cut Line= 4
     1639830.252      267620.856     1639978.114      267971.634
     1639979.686      268267.358     1640050.471      268434.095
#Sta/Elev= 30
      10 1046.64    90.2  993.37   110.2  986.63   170.3  945.17   190.3  930.23
   210.4  917.13   220.4  912.42   230.4  909.14   250.4   895.4   260.5  890.06
   270.5  888.06   300.5   885.8   528.5  881.66   558.1  880.35   577.7  877.51
   587.7  875.82   597.7  877.66   607.4   887.2   617.3   902.4   627.1  910.78
   646.8  916.81   656.7  917.53   696.5  928.86   706.6  932.63   736.8   947.1
   756.9  959.48     777  966.06   807.2  984.07   817.3  988.49   857.5 1001.61
#Mann= 3 , 0 , 0
      10     .06       0   577.7    .045       0   597.7     .06       0
Bank Sta=577.7,597.7
XS Rating Curve= 0 ,0
Exp/Cntr=0.3,0.1

Type RM Length L Ch R = 1 ,20230.5 ,566,560.2,554.5
XS GIS Cut Line= 4
     1639128.695      267965.342     1639315.882      268113.204
     1639504.641      268301.964     1639660.368       268504.88
#Sta/Elev= 30
     9.9  1064.9    59.6 1033.41    69.6 1026.27    79.5 1020.13   139.1  992.04
     159   986.9     169  980.42   178.9  972.75   268.2   919.4     288  905.58
   307.7  895.23   317.6  891.91   327.5  886.35   337.4  883.87   357.1  871.73
   367.1  869.47   377.1   869.5   505.5  880.87     535   886.9   564.5  889.66
   574.4  892.55   603.9  903.02   613.7  905.68   623.5  905.89   633.4  907.85
   653.1   908.7   692.4  928.03   721.9  946.51   731.8  951.37   761.3   963.9
#Mann= 3 , 0 , 0
       0     .06       0   357.1    .045       0   377.1     .06       0
Bank Sta=357.1,377.1
XS Rating Curve= 0 ,0
Exp/Cntr=0.3,0.1

Type RM Length L Ch R = 1 ,19670.3 ,781.4,814.5,847.5
XS GIS Cut Line= 4
     1638641.066      268300.391     1638955.665      268534.767
     1639158.582      268673.191     1639342.623      268844.648
#Sta/Elev= 30
    10.1  1099.1    50.3 1079.96    60.4 1069.85   100.6 1049.71   150.9 1028.35
   160.9 1022.32   191.1 1009.08   211.2  1004.7   231.4  996.51   281.7  972.31
   352.1   941.7   362.1  932.95   382.2  919.69   402.1  909.01   421.8  901.42
   451.3  884.95   461.1  871.46   470.7  864.86   480.7  864.01   490.7  865.27
   510.2  869.11   678.2   877.7   718.4  884.21   748.6  885.62   758.7  890.01
   768.7  897.77   798.9  914.51     819   922.2   879.4  954.34   889.5  960.85
#Mann= 3 , 0 , 0
       0     .08       0   470.7    .045       0   490.7     .06       0
Bank Sta=470.7,490.7
XS Rating Curve= 0 ,0
Exp/Cntr=0.3,0.1

Type RM Length L Ch R = 1 ,18855.8 ,687,641.6,596.2
XS GIS Cut Line= 4
     1638593.876      268682.629     1638589.157      268984.644
     1638545.113      269108.911     1638677.245      269329.131
#Sta/Elev= 30
    10.1  927.18    20.1  923.52    30.2  923.02   100.7  892.37   120.8  884.22
   130.9  884.02     151  877.13   221.5  869.58   231.6  869.56   271.8  867.33
   339.7     867   349.1  866.19   358.6     864   367.4  860.94   377.4  859.16
   387.4  859.69   405.6  863.45   415.1  867.45   433.9  882.42   443.8  880.14
   483.3  903.31   522.8  928.11   542.5  939.57   562.3  949.97   572.2   950.9
   582.1  955.65   601.8  965.94   611.7  971.92   621.6  978.54   690.7 1012.16
#Mann= 3 , 0 , 0
       0     .06       0   367.4    .045       0   387.4     .06       0
Bank Sta=367.4,387.4
XS Rating Curve= 0 ,0
Exp/Cntr=0.3,0.1

Type RM Length L Ch R = 1 ,18214.2 ,393.4,407.3,421.1
XS GIS Cut Line= 4
     1637920.633      269138.798     1638125.123      269256.773
     1638348.489      269294.525     1638538.821      269377.894
#Sta/Elev= 30
     9.8  988.32    19.7  982.35    29.5  977.59    39.3  973.67    49.2  966.26
     118  930.18   127.9  922.29   137.7  917.48   167.2  904.51   206.6  888.59
   226.2  877.85   245.9  871.14   275.5  862.21     295   855.1     305  852.37
     315  852.61   334.6  855.21   364.1  856.81   383.8  859.98   403.5  861.54
   462.6  864.25   502.2  864.91   512.1  866.17     522  869.42   531.9  874.02
   541.8  880.68   551.7  888.51     611  919.61   630.8  934.97   670.4  956.26
#Mann= 3 , 0 , 0
       0     .08       0     295    .045       0     315     .06       0
Bank Sta=295,315
XS Rating Curve= 0 ,0
Exp/Cntr=0.3,0.1