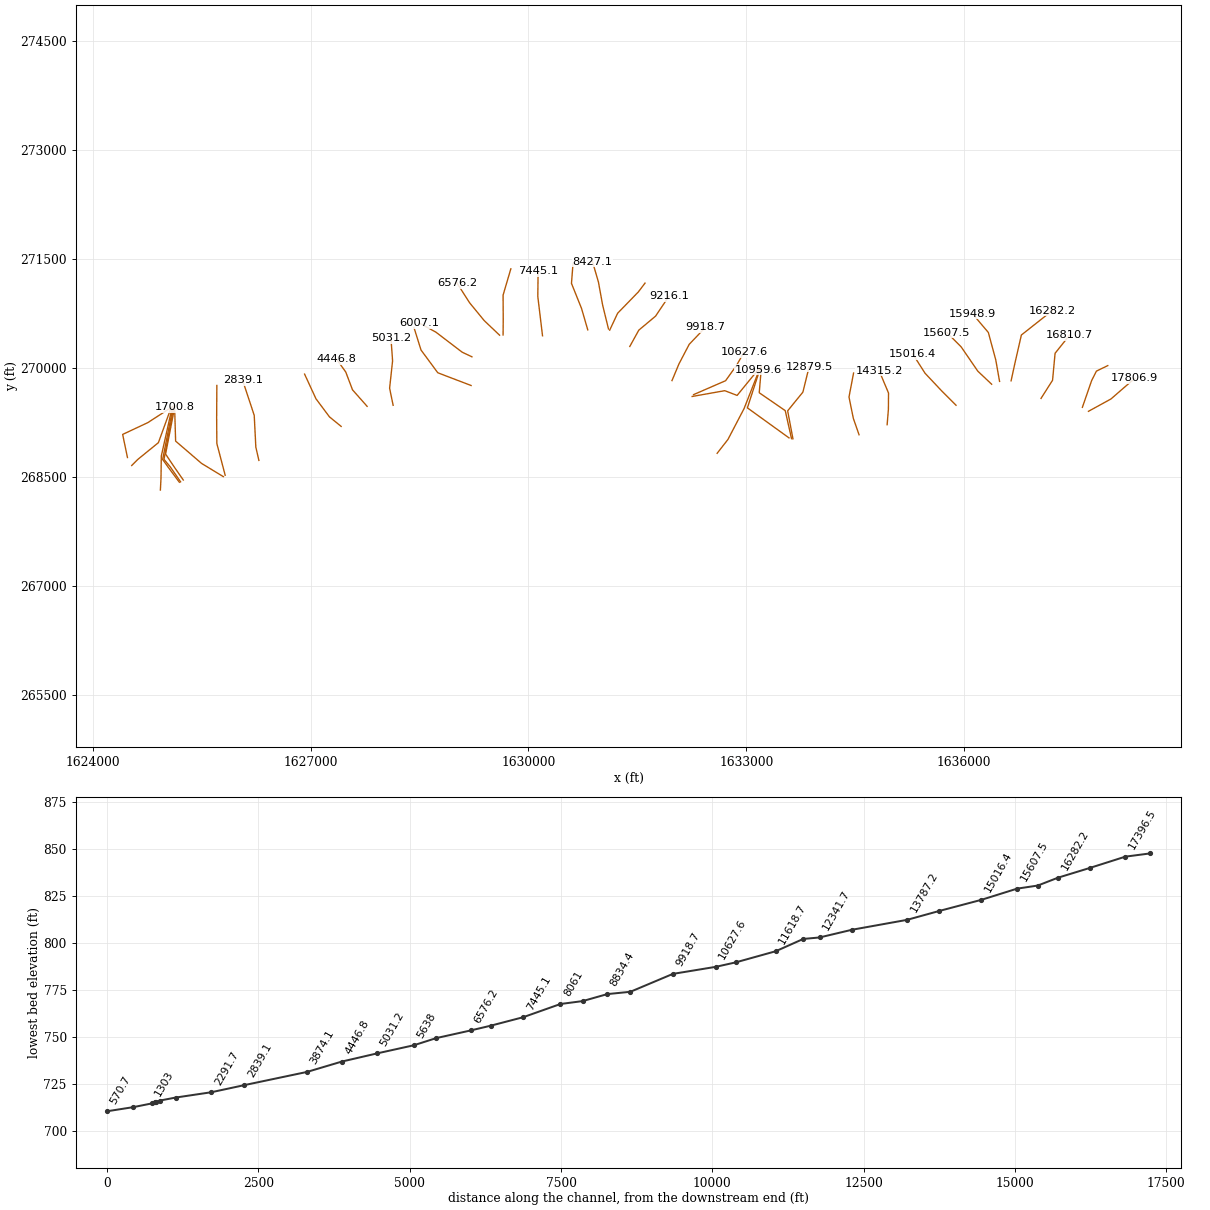
HEC-RAS study dmsfrk.prj: dmsfrk

--- dmsfrk.g01 (geometry) --- (continued)

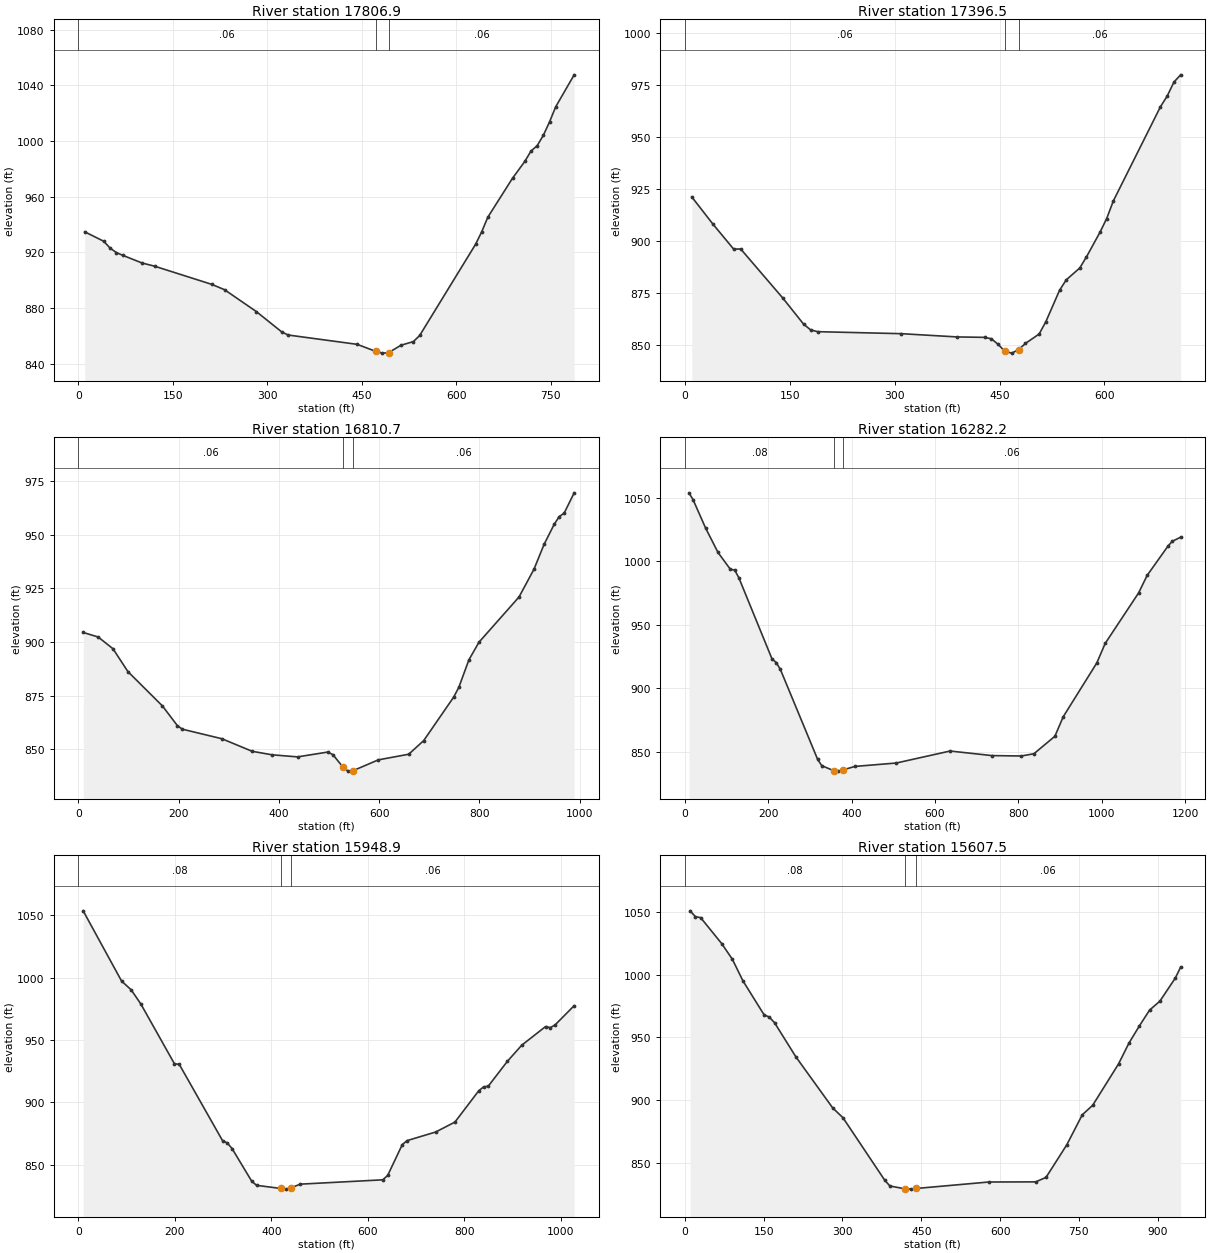
Type RM Length L Ch R = 1 ,17806.9 ,400.7,410.4,420.1
XS GIS Cut Line= 4
     1637711.425      269401.489     1638021.095      269571.031
     1638186.002      269714.361     1638349.367      269854.609
#Sta/Elev= 30
    10.1  934.74    40.3  927.96    50.4  923.03    60.5  919.78    70.6  917.83
   100.9  912.37     121  910.04   211.8  896.98     232  893.15   282.4  877.47
   322.8  862.82   332.9  860.61   442.4  853.92   472.2  848.82   482.2   847.6
   492.2  847.87   511.9  853.25   531.8  855.92   541.7  860.29   630.3  925.72
     640  934.65   649.8  945.23     689  973.22   708.5  985.28   718.3  992.74
   728.1  996.59   737.9 1004.05   747.7 1013.64   757.5 1024.52   786.8 1047.48
#Mann= 3 , 0 , 0
       0     .06       0   472.2    .045       0   492.2     .06       0
Bank Sta=472.2,492.2
XS Rating Curve= 0 ,0
Exp/Cntr=0.3,0.1

Type RM Length L Ch R = 1 ,17396.5 ,576.4,585.8,595.2
XS GIS Cut Line= 4
     1637628.056      269456.544     1637755.469      269824.625
     1637821.534      269955.184     1637977.261      270030.688
#Sta/Elev= 30
      10  921.06    39.9  908.11    69.9  895.92    79.9  896.02   139.8  872.51
   169.8  859.86   179.8  857.09   189.8  856.21   309.6  855.24   389.5  853.67
   428.5  853.47   438.3  852.79     448   850.1   457.5  846.78   467.5  845.88
   477.5  847.62   487.1  850.57   506.6  855.06   516.3  861.07   535.8  876.12
   545.4  881.16   564.7  886.85   574.3  892.21   593.5  903.99   603.1   910.6
   612.8   919.2   680.1  964.49   689.7  969.59   699.3  976.32   708.9  979.82
#Mann= 3 , 0 , 0
       0     .06       0   457.5    .045       0   477.5     .06       0
Bank Sta=457.5,477.5
XS Rating Curve= 0 ,0
Exp/Cntr=0.3,0.1

Type RM Length L Ch R = 1 ,16810.7 ,531.8,528.5,525.2
XS GIS Cut Line= 4
     1637058.631      269579.237     1637217.504      269829.344
     1637252.109      270200.571      1637451.88      270450.678
#Sta/Elev= 30
     9.9  904.41    39.5  902.32    69.1  896.86    98.8  886.25   167.9   870.2
   197.5   861.1   207.4  859.41   286.4  854.97   346.7  849.12     387  847.47
   437.4  846.52   497.8  848.77   507.9  847.55   528.1  841.73   538.1  839.89
   548.1   840.1   598.6  845.14   659.1  847.75   689.1  854.12   749.2  874.46
   759.2  878.95   779.2  891.68   799.2  899.86   879.2  920.94   909.2  933.94
   929.2  945.43   949.2  954.68   959.2  958.31   969.2  959.93   989.2  969.41
#Mann= 3 , 0 , 0
       0     .06       0   528.1    .045       0   548.1     .06       0
Bank Sta=528.1,548.1
XS Rating Curve= 0 ,0
Exp/Cntr=0.3,0.1

Type RM Length L Ch R = 1 ,16282.2 ,321.2,333.3,345.5
XS GIS Cut Line= 4
     1636646.506      269821.479      1636701.56      270074.731
     1636788.075      270452.251     1637214.358      270788.872
#Sta/Elev= 30
      10 1053.96    19.9 1048.51    49.8 1026.29    79.7 1006.95   109.6  993.58
   119.6   993.2   129.6   987.1   209.3  923.05   219.3  920.27   229.3  914.82
   318.8  843.87   328.7  838.97   358.4  834.89   368.4  834.68   378.4  835.54
   408.1  838.38   507.4  841.07   636.5  850.52     737  846.92   807.4  846.61
   837.6  848.37   887.9  862.15     908  877.57   988.5  919.93  1008.6   935.3
  1089.1  975.27  1109.2  988.86  1159.5  1012.1  1169.5 1015.74  1189.6 1019.01
#Mann= 3 , 0 , 0
       0     .08       0   358.4    .045       0   378.4     .06       0
Bank Sta=358.4,378.4
XS Rating Curve= 0 ,0
Exp/Cntr=0.3,0.1

Type RM Length L Ch R = 1 ,15948.9 ,332.9,341.4,349.8
XS GIS Cut Line= 4
     1636487.633      269813.614     1636435.724      270107.764
     1636333.479      270486.857     1636116.405      270743.255
#Sta/Elev= 30
      10 1053.57    89.6  997.29   109.5  990.24   129.4  978.97   199.1     931
   209.1  930.53   298.7  869.42   308.8  867.49   318.8  862.85   359.1  836.94
   369.2  833.56   419.6  831.03   429.6  830.51   439.6  831.39   459.8   834.5
   630.9  837.97     641  841.54   671.2  866.22   681.3  869.41   740.7  876.34
   780.3  884.26   829.7   909.4   839.5  912.39   849.4  913.06     889  932.98
   918.6  945.83     968  960.81   977.9  959.95   987.8  962.12  1027.3  977.55
#Mann= 3 , 0 , 0
       0     .08       0   419.6    .045       0   439.6     .06       0
Bank Sta=419.6,439.6
XS Rating Curve= 0 ,0
Exp/Cntr=0.3,0.1

Type RM Length L Ch R = 1 ,15607.5 ,587.2,591.1,595.1
XS GIS Cut Line= 4
     1636379.096      269774.289     1636188.763      269953.611
     1635959.106      270288.659     1635764.054      270483.711
#Sta/Elev= 30
    10.1 1050.81    20.1 1046.19    30.2 1045.36    70.4 1024.58    90.5 1012.17
   110.6     995   150.9  967.87   160.9  966.07     171  961.46   211.2  934.47
   281.3  893.71   301.1  885.75   380.4  836.01   390.3  831.37   419.9  829.04
   429.9  828.87   439.9  829.38   578.5  834.55   667.7  834.65   687.4  838.25
   726.8  864.16   756.4  888.18   776.1  895.71   825.3  928.66     845   945.2
   864.7  958.82   884.4  971.63   904.1   978.8   933.7  997.42   943.5 1005.95
#Mann= 3 , 0 , 0
       0     .08       0   419.9    .045       0   439.9     .06       0
Bank Sta=419.9,439.9
XS Rating Curve= 0 ,0
Exp/Cntr=0.3,0.1

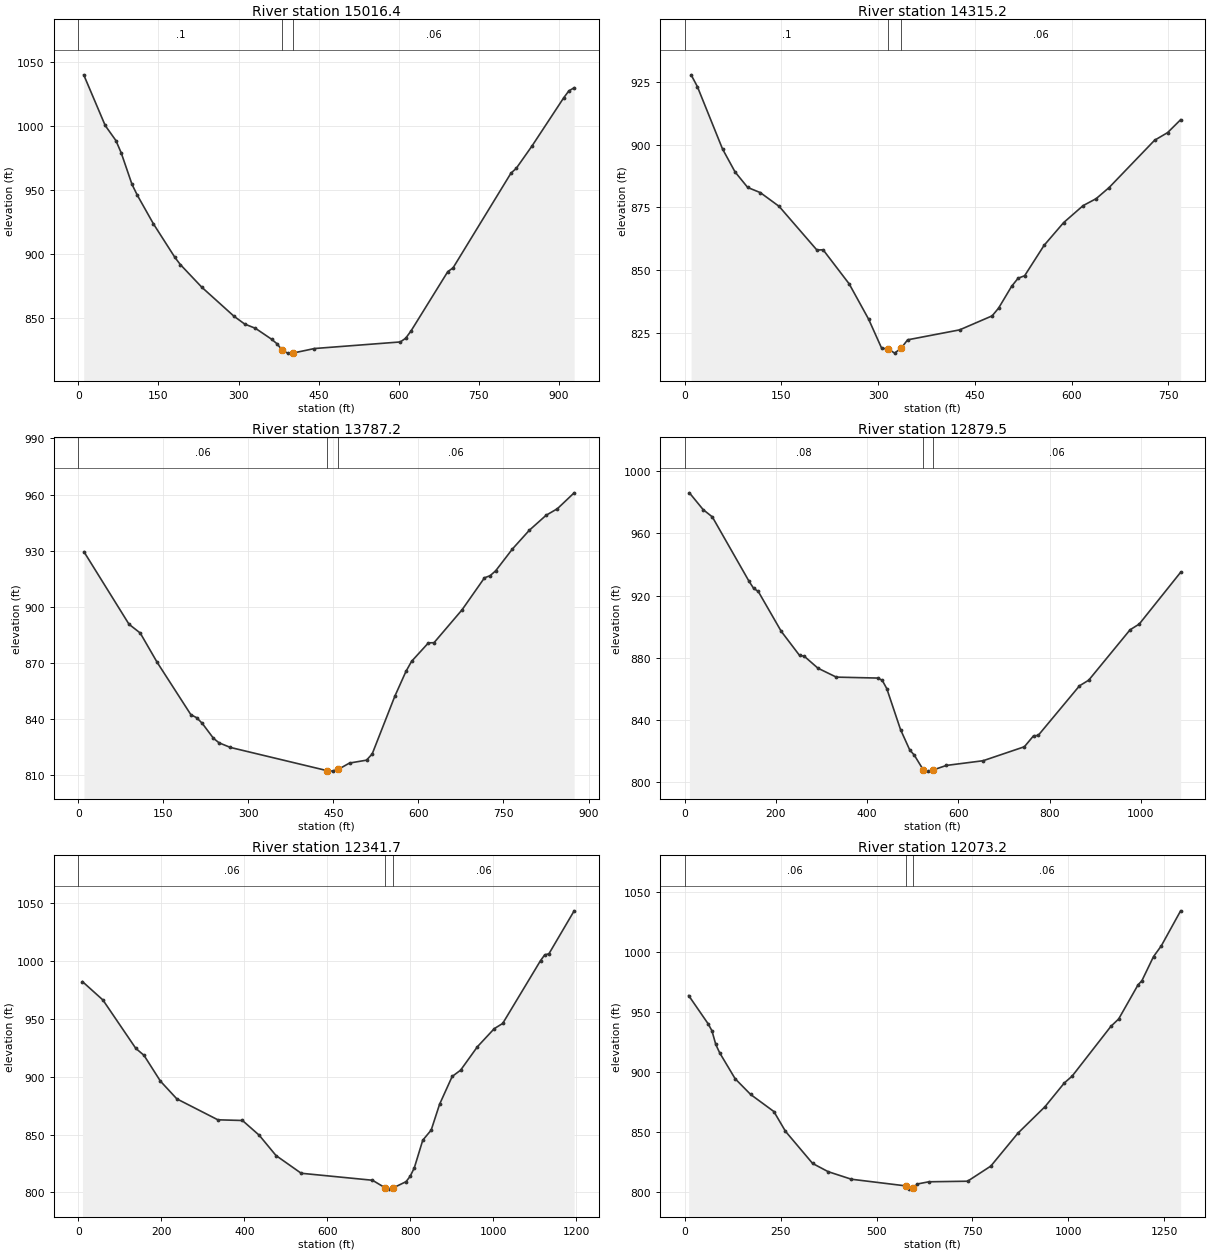
Type RM Length L Ch R = 1 ,15016.4 ,720.3,701.2,682
XS GIS Cut Line= 4
     1635888.321      269484.857     1635696.415      269676.763
     1635462.039      269925.297     1635292.155      270191.133
#Sta/Elev= 30
    10.1 1040.07    50.3 1000.54    70.4  988.76    80.4  979.07   100.5   954.6
   110.6  946.03   140.7  923.75   180.9  897.57     191  892.03   231.2  874.34
   291.5  851.69   311.6  845.58   331.7  842.27   361.8  833.78   371.9  830.27
     382  825.12     392  822.91     402  822.96   442.2   826.5     603  831.64
     613  834.54   622.9  840.15   691.9  886.53   701.7  889.43   810.2  963.37
     820  967.06   849.6  984.57   908.8 1022.06   918.6 1027.57   928.5 1029.98
#Mann= 3 , 0 , 0
       0      .1       0     382    .045       0     402     .06       0
Bank Sta=382,402
XS Rating Curve= 0 ,0
Exp/Cntr=0.3,0.1

Type RM Length L Ch R = 1 ,14315.2 ,522.8,528,533.3
XS GIS Cut Line= 4
     1634939.804      269217.448     1634957.107      269431.376
     1634958.679      269653.168     1634829.694      269959.903
#Sta/Elev= 30
     9.8  927.81    19.5  923.12    58.5  898.29      78  889.12    97.6  882.94
   117.1   880.9   146.3  875.42   204.9  858.03   214.6  858.11     255  844.54
   285.2  830.46   305.4  818.88   315.5  818.67   325.5  816.95   335.5  818.89
   345.7  822.25   426.3  826.21   476.8   831.8   486.8  834.88     507  843.56
   517.1   846.8   527.2  847.77   557.4  859.89   587.7  868.94   617.9  875.71
   638.1  878.47   658.3  882.92   728.8  901.75     749  904.79   769.2  909.93
#Mann= 3 , 0 , 0
       0      .1       0   315.5    .045       0   335.5     .06       0
Bank Sta=315.5,335.5
XS Rating Curve= 0 ,0
Exp/Cntr=0.3,0.1

Type RM Length L Ch R = 1 ,13787.2 ,930.2,907.6,885
XS GIS Cut Line= 4
     1634552.846      269079.024     1634474.197      269303.963
     1634414.422      269598.113     1634477.342      269928.443
#Sta/Elev= 30
     9.9  929.44    89.4  890.72   109.2  886.02     139   870.4   198.6  842.38
   208.5  840.85   218.4  837.86   238.3  829.83   248.3  827.37   268.3  824.91
   438.4  812.55   448.4  812.26   458.4  813.18   478.4  816.57   508.4  818.12
   518.4  821.44   558.2  852.17     578  865.55   587.9  870.91   617.6  880.77
   627.5  880.86   676.9  898.41   716.5  915.52   726.4  916.64   736.3  919.28
   765.9  930.95   795.6  940.92   825.3  948.94   845.1  952.42   874.7  960.91
#Mann= 3 , 0 , 0
       0     .06       0   438.4    .045       0   458.4     .06       0
Bank Sta=438.4,458.4
XS Rating Curve= 0 ,0
Exp/Cntr=0.3,0.1

Type RM Length L Ch R = 1 ,12879.5 ,496.2,537.8,579.4
XS GIS Cut Line= 4
     1633642.605      269022.484     1633569.898      269408.392
     1633779.631      269665.665      1633866.32      270018.016
#Sta/Elev= 30
    10.1  986.15    40.3  975.33    60.4  970.65     141  929.15     151  924.67
   161.1  922.68   211.5  897.01   251.7  881.49   261.8  881.02     292  873.28
   332.3  867.52   422.9  866.92   432.9  865.52     443  860.15   473.2  833.74
   493.3  820.68   503.3  817.33   523.5  807.61   533.5  807.01   543.5  807.66
   573.8  810.68   654.2   813.7   744.8   822.7   764.9  829.74     775  829.96
   865.7  861.94   885.9  865.55   976.6  897.98   996.8   901.7  1087.5     935
#Mann= 3 , 0 , 0
       0     .08       0   523.5    .045       0   543.5     .06       0
Bank Sta=523.5,543.5
XS Rating Curve= 0 ,0
Exp/Cntr=0.3,0.1

Type RM Length L Ch R = 1 ,12341.7 ,269.1,268.5,267.9
XS GIS Cut Line= 4
      1633623.03       269025.28      1633536.34      269411.189
     1633178.396      269657.275     1633209.157      270020.813
#Sta/Elev= 30
     9.9  981.96    59.3  966.07   138.4  924.37   158.2  918.35   197.8  896.07
   237.3  880.79   336.2  862.71   395.5  862.12   435.9  849.38   476.3  831.89
     537  816.59   708.7  810.56   739.1  804.09   749.1   802.9   759.1  804.04
   789.5  809.31   799.6  813.97   809.7  821.44   829.9  845.12   850.2  853.84
   870.4   876.1   900.8  900.13   921.1  905.54   961.6  925.76  1002.2  941.38
  1022.5  945.85  1113.7 1000.08  1123.8 1005.03  1133.9 1005.96  1194.7 1043.02
#Mann= 3 , 0 , 0
       0     .06       0   739.1    .045       0   759.1     .06       0
Bank Sta=739.1,759.1
XS Rating Curve= 0 ,0
Exp/Cntr=0.3,0.1

Type RM Length L Ch R = 1 ,12073.2 ,490.9,454.5,418.2
XS GIS Cut Line= 3
     1633588.774      269035.417      1633015.32       269449.02
     1633196.098      270006.387
#Sta/Elev= 30
    10.1  963.68    60.6  940.22    70.7  934.34    80.8  922.86    90.9  915.91
   131.3  894.25   171.7  881.12   232.3  866.88   262.6  850.35   333.3  823.56
   373.7  816.71   434.3  810.39   575.8  804.84   585.8  802.12   595.8  802.88
     606  806.37   636.3  808.25   737.4  808.72     798  821.35   868.7  848.81
   939.4  870.95   989.9  890.79  1010.1  896.43  1111.2  937.99  1131.4  944.12
  1181.9  972.58    1192  976.06  1222.3  996.19  1242.5 1005.11    1293 1034.38
#Mann= 3 , 0 , 0
       0     .06       0   575.8    .045       0   595.8     .06       0
Bank Sta=575.8,595.8
XS Rating Curve= 0 ,0
Exp/Cntr=0.3,0.1

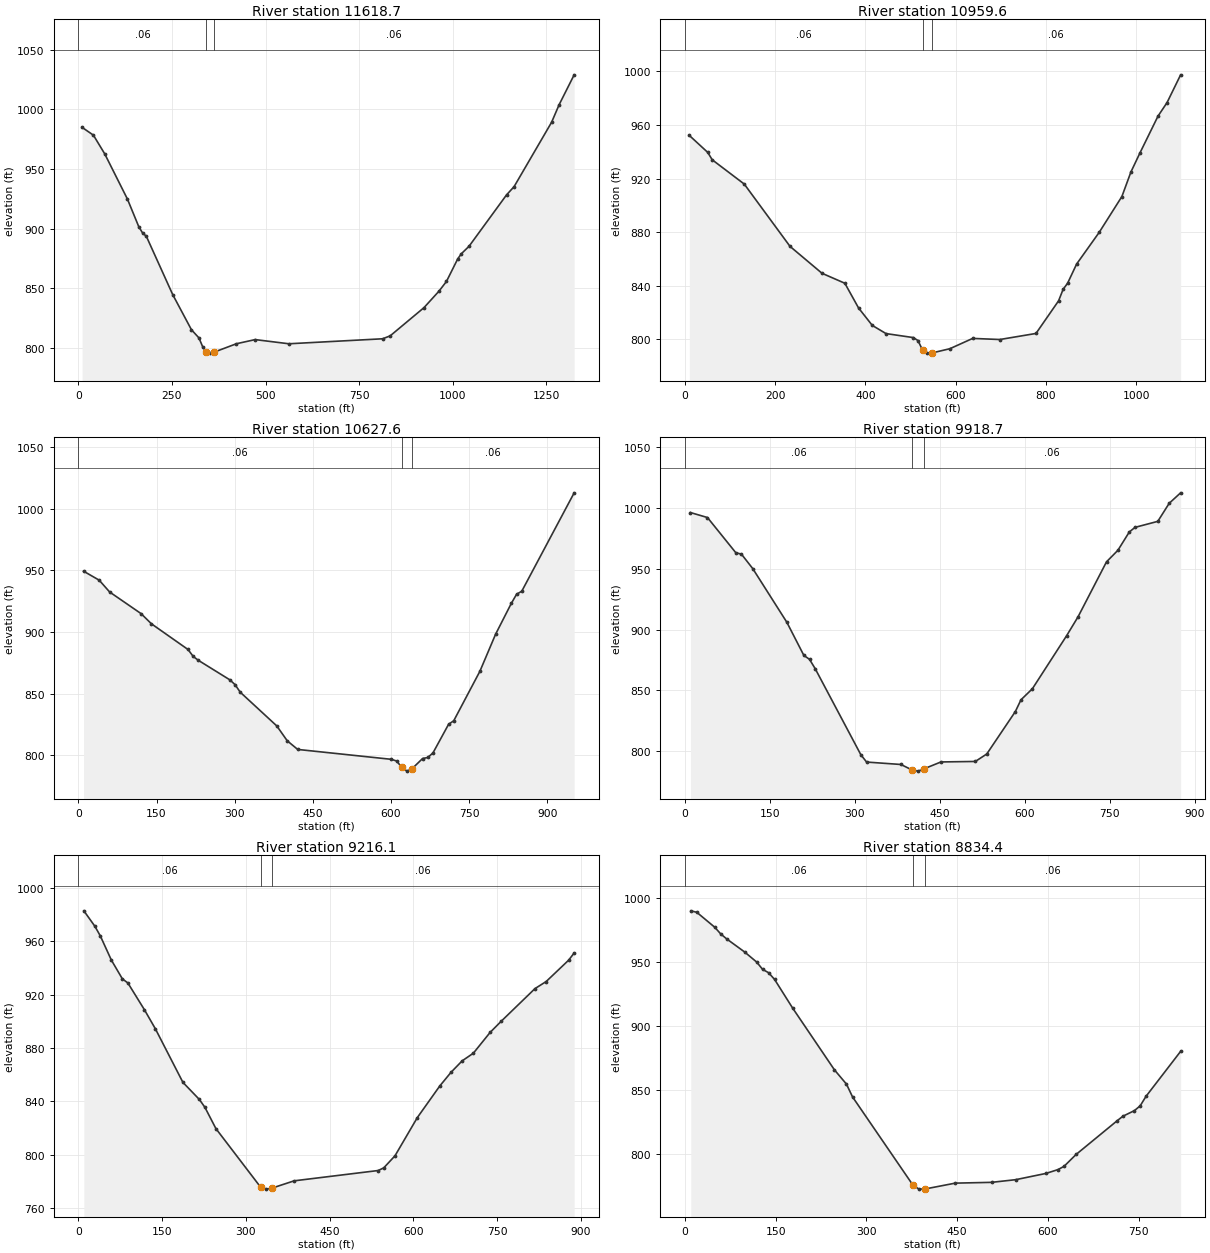
Type RM Length L Ch R = 1 ,11618.7 ,696.3,659,621.8
XS GIS Cut Line= 4
     1632598.834      268823.587     1632747.745      269014.444
     1632970.062      269440.202     1633190.281      270000.189
#Sta/Elev= 30
    10.1  984.77    40.3  978.24    70.6  962.52   131.1  924.71   161.4  901.55
   171.5  896.34   181.6  893.51   252.1  844.61   302.1  815.17   322.1  808.35
   332.1  800.89   342.1  796.42   352.1  795.59   362.1  796.36   422.2  803.46
   472.2  806.93   562.3  803.43   812.6  807.61   832.7  810.05     923  833.69
   963.1  847.51   983.1  855.67  1013.2   874.6  1023.2  878.99  1043.3  885.11
  1143.6  928.23  1163.7  935.11  1263.9  989.09    1284 1003.81  1324.1 1028.82
#Mann= 3 , 0 , 0
       0     .06       0   342.1    .045       0   362.1     .06       0
Bank Sta=342.1,362.1
XS Rating Curve= 0 ,0
Exp/Cntr=0.3,0.1

Type RM Length L Ch R = 1 ,10959.6 ,298.3,332,365.7
XS GIS Cut Line= 4
     1632254.872      269605.891     1632703.701       269685.59
     1632873.584      269620.572     1633165.113      269977.118
#Sta/Elev= 30
    10.1  952.19    50.7  939.59    60.8  934.02   131.7  915.91     233  869.41
   303.9   849.3   354.5  841.86   384.9  823.39   415.3  810.38   445.7  804.27
   506.4  801.28   516.5  799.06   526.7  791.91   536.7  789.68   546.7  789.74
   587.2  792.98   637.7  800.67   697.8  799.84   777.9  804.37     828  828.75
     838  837.31     848  841.91     868  856.23   918.1  879.94   968.2   906.6
   988.2  924.94  1008.2  939.14  1048.2  966.64  1068.3  976.79  1098.3  997.47
#Mann= 3 , 0 , 0
       0     .06       0   526.7    .045       0   546.7     .06       0
Bank Sta=526.7,546.7
XS Rating Curve= 0 ,0
Exp/Cntr=0.3,0.1

Type RM Length L Ch R = 1 ,10627.6 ,705.6,708.9,712.2
XS GIS Cut Line= 4
      1632274.18      269631.337     1632715.302      269823.129
     1632865.996        270034.1     1632970.112      270217.673
#Sta/Elev= 30
      10  949.28    40.1  941.96    60.1   932.4   120.3  914.91   140.3  906.62
   210.4  885.84   220.5  880.16   230.5  876.99   290.6  861.27   300.6   857.4
   310.7  851.21   380.8  823.89   400.8  811.87   420.9  804.86   600.7  796.85
   610.6  795.48   620.6  790.41   630.6  787.29   640.6  789.37   660.5   797.5
   670.5  798.34   680.4  802.03   710.4  825.25   720.3  828.12   770.4  868.14
   800.6  898.23   830.7  923.17   840.8  930.55   850.8  933.05   951.3 1012.75
#Mann= 3 , 0 , 0
       0     .06       0   620.6    .045       0   640.6     .06       0
Bank Sta=620.6,640.6
XS Rating Curve= 0 ,0
Exp/Cntr=0.3,0.1

Type RM Length L Ch R = 1 ,9918.7  ,712.9,702.6,692.4
XS GIS Cut Line= 4
     1631977.093      269824.712      1632073.57      270055.419
     1632214.091      270323.877     1632436.408       270556.68
#Sta/Elev= 30
      10  996.39      40  992.29      90  963.34     100  962.13     120   950.2
     180  906.15   210.1   878.8   220.1  875.56   230.1  867.88   310.7  797.02
   320.8  791.01   381.4  789.01   401.7  784.36   411.7  783.54   421.7  785.36
   452.1   791.1   512.7   791.5   532.9  797.65   583.3  832.56   593.3  842.28
   613.4  851.35   673.8     895   693.9   910.5   744.2  955.82   764.3  965.33
   784.4  980.39   794.5   984.2   834.7  989.14   854.9 1004.05     875 1012.63
#Mann= 3 , 0 , 0
       0     .06       0   401.7    .045       0   421.7     .06       0
Bank Sta=401.7,421.7
XS Rating Curve= 0 ,0
Exp/Cntr=0.3,0.1

Type RM Length L Ch R = 1 ,9216.1  ,379.1,381.8,384.4
XS GIS Cut Line= 4
     1631396.132      270294.514     1631519.875      270518.928
     1631750.581      270711.883     1631935.146      270986.633
#Sta/Elev= 30
     9.9  982.99    29.6  971.42    39.4  964.13    59.1  946.04    78.9  931.88
    88.7  928.83   118.3  908.76     138  894.39   187.3  854.18   216.8  841.32
   226.7  835.45   246.4  819.46   326.5  775.48   336.5  774.02   346.5  774.74
   386.6  780.26     537  787.99     547  789.99   567.1  799.03   607.2  827.79
   647.3  851.45   667.4   861.7   687.4  870.33   707.5   876.1   737.6  891.74
   757.6  900.17   817.8  924.58   837.9  929.91     878  945.89     888  951.34
#Mann= 3 , 0 , 0
       0     .06       0   326.5    .045       0   346.5     .06       0
Bank Sta=326.5,346.5
XS Rating Curve= 0 ,0
Exp/Cntr=0.3,0.1

Type RM Length L Ch R = 1 ,8834.4  ,382,407.3,432.5
XS GIS Cut Line= 4
     1631119.285      270518.928     1631228.346      270751.732
     1631513.583      271045.358     1631605.865      271167.003
#Sta/Elev= 30
     9.9  989.65    19.8  988.51    49.4  976.89    59.3  971.67    69.2  967.77
    98.9  957.55   118.7  949.75   128.5  944.05   138.4  941.43   148.3   936.2
     178  913.98   247.2  865.73   267.1  854.61   277.1  844.65   376.9   775.9
   386.9  772.79   396.9  772.91   446.8  777.46   506.7  778.07   546.6  780.15
   596.6  785.02   616.5  788.01   626.5  790.54   646.5  799.84   714.2  826.06
   723.7  829.59   742.8  833.98   752.3  837.71   761.9  845.08   819.1  880.14
#Mann= 3 , 0 , 0
       0     .06       0   376.9    .045       0   396.9     .06       0
Bank Sta=376.9,396.9
XS Rating Curve= 0 ,0
Exp/Cntr=0.3,0.1

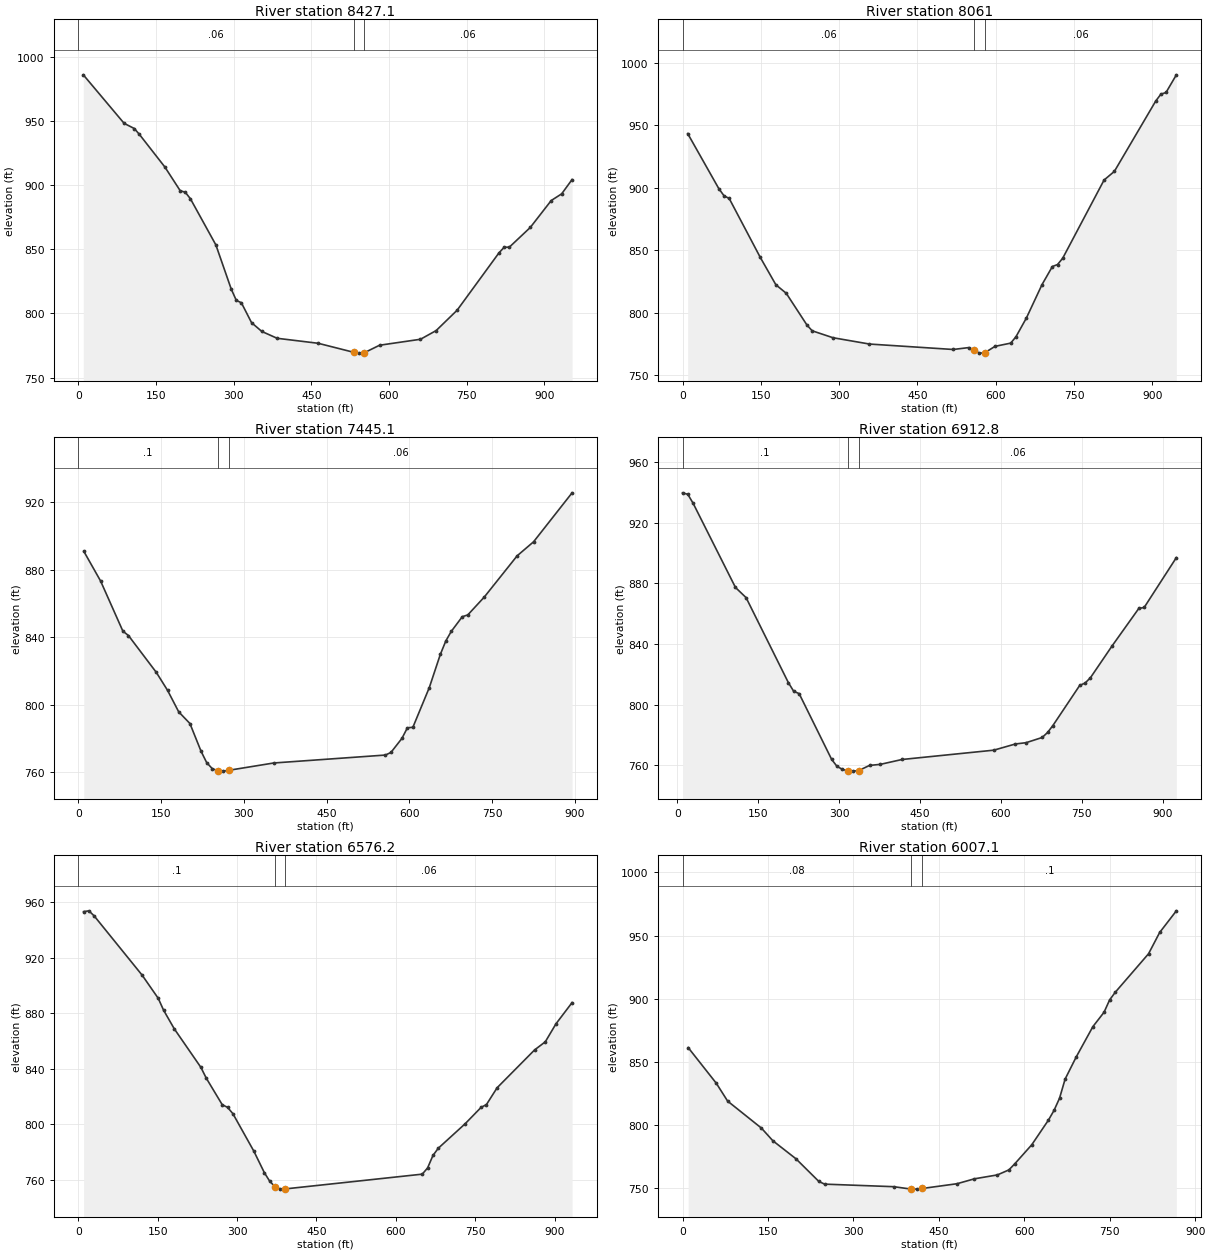
Type RM Length L Ch R = 1 ,8427.1  ,362.5,366.1,369.7
XS GIS Cut Line= 4
     1631102.506      270535.707     1631022.808      270860.793
     1630964.082      271181.685     1630882.287      271462.727
#Sta/Elev= 30
     9.8  986.25    88.6  948.39   108.3  944.33   118.1  939.77   167.4  914.25
   196.9  895.81   206.7  894.61   216.6  889.55   265.8   853.5   295.3   819.2
   305.2  810.24     315  808.39   334.7  792.83   354.5  785.99   384.1  780.65
   463.2  776.76   532.3  769.68   542.3  769.07   552.3  769.36   581.8  775.22
   660.9  779.89   691.2  786.69   731.6  802.54   812.3  847.24   822.4  851.66
   832.5  851.78   872.9  867.14   913.3  888.14   933.5  893.38   953.6  904.53
#Mann= 3 , 0 , 0
       0     .06       0   532.3    .045       0   552.3     .06       0
Bank Sta=532.3,552.3
XS Rating Curve= 0 ,0
Exp/Cntr=0.3,0.1

Type RM Length L Ch R = 1 ,8061    ,621.1,615.9,610.8
XS GIS Cut Line= 4
     1630817.269      270523.123     1630731.279      270818.846
     1630592.855      271162.809     1630613.828       271429.17
#Sta/Elev= 30
     9.9  943.34    69.5  899.25    79.5  893.52    89.4  891.38     149  844.13
   178.8  822.27   198.7  815.44   238.4  789.98   248.4   785.4   288.1  779.87
   358.1   774.8   518.4  770.45   548.5  771.98   558.5  770.08   568.5  767.53
   578.5  767.73   598.6  772.96   628.6  775.54   638.7  780.65   658.7   795.7
   688.6  822.41   708.4  836.87   718.3  838.46   728.2  843.51   807.4   906.1
   827.2  913.07   906.3  969.32   916.2  974.85   926.1  976.21   945.9  990.36
#Mann= 3 , 0 , 0
       0     .06       0   558.5    .045       0   578.5     .06       0
Bank Sta=558.5,578.5
XS Rating Curve= 0 ,0
Exp/Cntr=0.3,0.1

Type RM Length L Ch R = 1 ,7445.1  ,536.5,532.3,528
XS GIS Cut Line= 3
     1630194.362      270441.327     1630129.345      270982.438
      1630133.54      271330.595
#Sta/Elev= 30
    10.1  890.95    40.5  873.34    80.9  843.59      91  840.97   141.6  819.06
   161.9  808.44   182.1  795.68   202.4  788.77   222.6   772.3   232.8  765.56
   242.9  761.98   253.2  760.76   263.2  760.51   273.2  761.02   354.3  765.34
   556.7  770.05   566.7  771.59   586.6  779.92   596.5   786.2   606.5  786.53
   636.3  810.13   656.2  829.74   666.2  837.77   676.1  843.45     696  852.14
     706   853.2   735.8  863.77   795.5  888.29   825.3  896.62     895  925.65
#Mann= 3 , 0 , 0
       0      .1       0   253.2    .045       0   273.2     .06       0
Bank Sta=253.2,273.2
XS Rating Curve= 0 ,0
Exp/Cntr=0.3,0.1

Type RM Length L Ch R = 1 ,6912.8  ,319.5,336.6,353.7
XS GIS Cut Line= 4
     1629651.154      270453.911     1629653.251      270669.936
     1629651.154      271001.314     1629758.118      271364.152
#Sta/Elev= 30
     9.8  939.89    19.6   938.9    29.5  932.96     108  877.37   127.7  870.65
   206.2  814.43     216  808.78   226.1  807.24   286.3  763.83   296.4  759.12
   306.4  757.21   316.5  756.23  326.53  756.03   336.5  756.38   356.6   759.8
   376.7   760.5   416.9  763.72   587.2  769.88   627.1  773.96     647  774.82
   676.8  778.25   686.8  781.55   696.7  786.14   746.5  812.68   756.5  814.23
   766.4  817.77   806.2   838.6     856  863.49     866  864.15   925.7   897.1
#Mann= 3 , 0 , 0
     9.8      .1       0   316.5    .045       0   336.5     .06       0
Bank Sta=316.5,336.5
XS Rating Curve= 0 ,0
Exp/Cntr=0.3,0.1

Type RM Length L Ch R = 1 ,6576.2  ,563.1,569.1,575
XS GIS Cut Line= 4
     1629602.915      270449.717     1629391.085       270651.06
     1629189.741      270896.448     1629015.663      271169.101
#Sta/Elev= 30
    10.1   953.1    20.2  953.68    30.2  949.99   120.9  907.32   151.2  890.73
   161.2  882.25   181.4  868.84   231.8  841.05   241.9  833.33   272.1  814.21
   282.2  812.29   292.3  807.72   331.9  780.74   351.8  765.22   361.7  759.24
   371.5  755.26   381.5  753.46   391.5  753.63   650.1  764.23   660.2  768.72
   670.3  777.67   680.4  782.89     731  800.44   761.3  812.28   771.4   814.3
   791.6  826.41   862.4  853.62   882.6  859.45   902.8  872.41   933.2  887.66
#Mann= 3 , 0 , 0
       0      .1       0   371.5    .045       0   391.5     .06       0
Bank Sta=371.5,391.5
XS Rating Curve= 0 ,0
Exp/Cntr=0.3,0.1

Type RM Length L Ch R = 1 ,6007.1  ,376.4,369.2,361.9
XS GIS Cut Line= 4
     1629222.134      270152.245     1629087.905      270215.631
     1628726.232      270491.547     1628495.059      270618.319
#Sta/Elev= 30
     9.9  861.42    59.4  833.12    79.2  819.05   138.5   797.7   158.6  787.67
     199  773.47   239.4  755.45   249.5  753.34   370.8  751.32   401.3  749.41
   411.3  749.39   421.3  749.93     482  753.67   512.4  757.54   552.8  760.64
     573  764.61   583.1  769.32   613.1  784.47   642.4  804.01   652.2  811.66
   661.9  821.32   671.7  836.48   691.2  854.01   720.5  878.02   740.1  889.41
   749.8   899.1   759.6  905.12   818.2  935.68   837.7   952.5     867  969.63
#Mann= 3 , 0 , 0
       0     .08       0   401.3    .045       0   421.3      .1       0
Bank Sta=401.3,421.3
XS Rating Curve= 0 ,0
Exp/Cntr=0.3,0.1

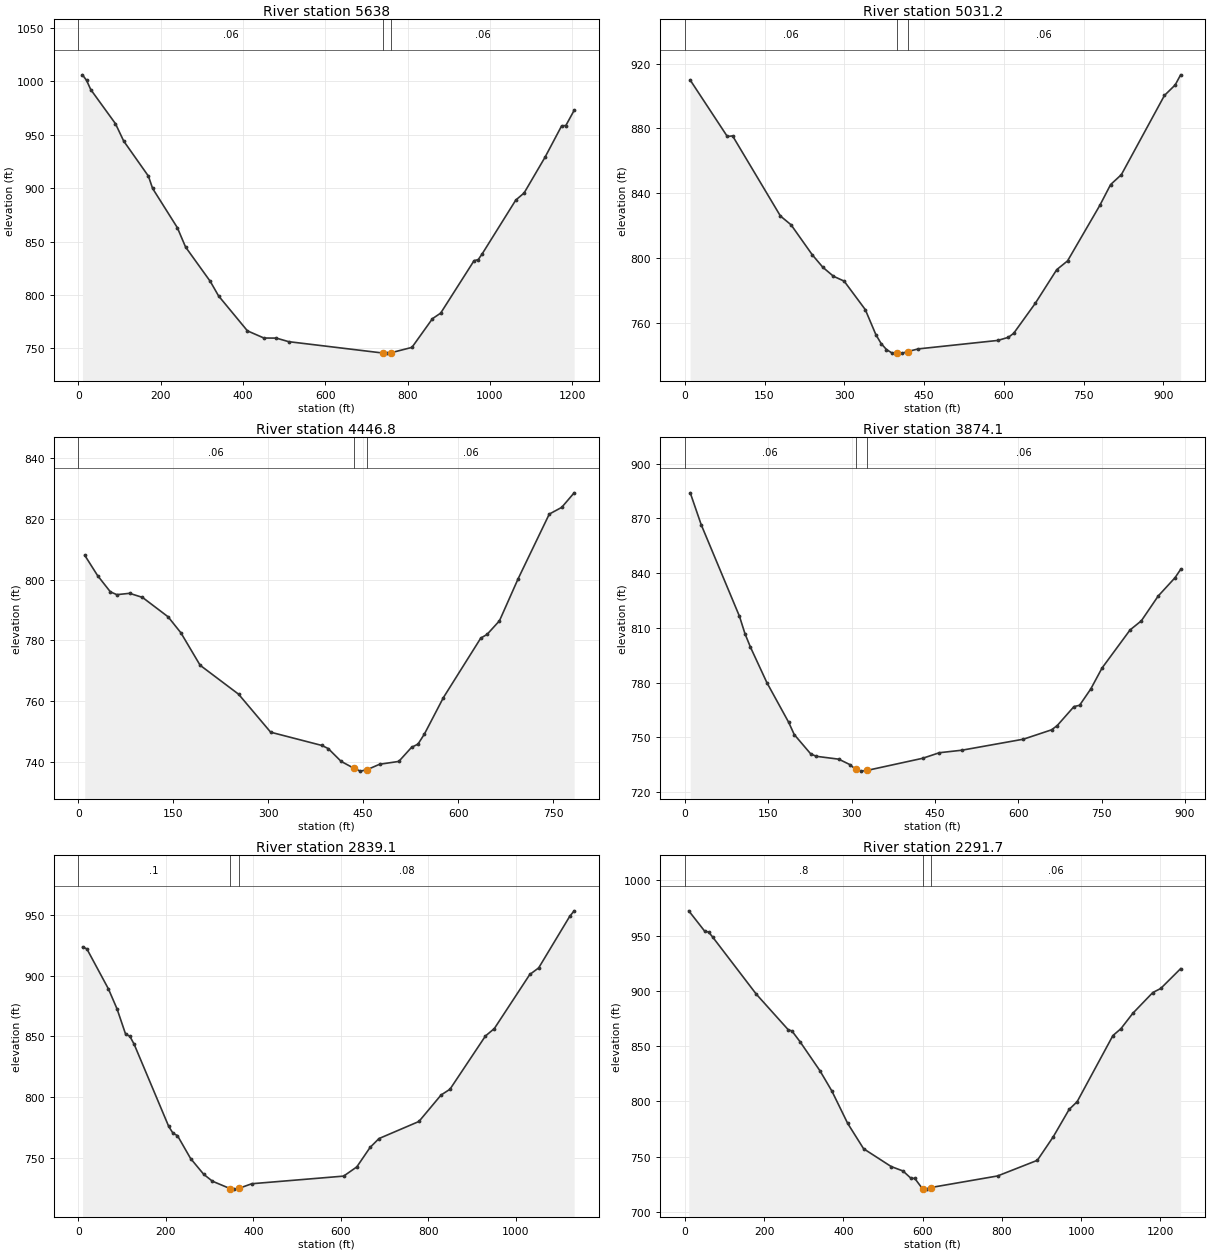
Type RM Length L Ch R = 1 ,5638    ,625.8,606.8,587.7
XS GIS Cut Line= 4
     1629210.948      269757.015     1628752.332      269932.259
     1628521.159       270245.46     1628424.216      270554.933
#Sta/Elev= 30
      10 1006.07      20 1000.88    30.1  992.31    90.2  960.34   110.2   944.1
   170.3  911.23   180.4  899.77   240.5  863.04   260.5  844.91   320.6  812.69
   340.7  799.13   410.8  766.44   450.9  759.72   480.9  759.66   510.9  756.33
   740.5  745.64   750.5  745.59   760.5  746.03   810.4  750.96   860.3  777.85
   880.2  783.03   961.3  832.11   971.4   833.1   981.6  838.82  1062.7  888.86
  1082.9  895.48  1133.6  928.85  1174.1  958.32  1184.3  958.61  1204.5  972.84
#Mann= 3 , 0 , 0
       0     .06       0   740.5    .045       0   760.5     .06       0
Bank Sta=740.5,760.5
XS Rating Curve= 0 ,0
Exp/Cntr=0.3,0.1

Type RM Length L Ch R = 1 ,5031.2  ,572.6,584.4,596.2
XS GIS Cut Line= 4
     1628137.115      269484.828     1628088.643      269719.729
     1628129.658      270096.316     1628107.286      270409.518
#Sta/Elev= 30
      10  909.93      80  875.02    89.9  875.39   179.9  825.92   199.9  820.49
   239.8  801.98   259.8  794.23   279.7  788.72   299.7  785.74   339.5  768.15
   359.5  752.63   369.4  747.15   379.4  743.49   389.4  741.42   399.3  741.39
   409.3  741.27   419.3  742.25   439.2  743.88   588.8  749.11   608.7  751.03
   618.7  753.52   659.2  771.98   699.7  792.82     720  798.21   780.7  832.49
     801  845.34   821.2  851.44   902.3  900.37   922.5  906.85   932.7  913.09
#Mann= 3 , 0 , 0
       0     .06       0   399.3    .045       0   419.3     .06       0
Bank Sta=399.3,419.3
XS Rating Curve= 0 ,0
Exp/Cntr=0.3,0.1

Type RM Length L Ch R = 1 ,4446.8  ,565.7,572.8,579.8
XS GIS Cut Line= 4
     1627779.171      269469.914     1627577.827      269697.358
     1627484.613      269943.445     1627357.841      270118.688
#Sta/Elev= 30
    10.1  808.06    30.4  801.36    50.6     796    60.8  795.07      81  795.51
   101.3  794.17   141.8  787.77     162   782.5   192.4   771.8   253.1  762.27
   303.8  749.74   384.7  745.37   394.8  744.34   415.1  740.12   435.5  737.83
   445.5  736.91   455.5  737.33   475.8  739.17   506.2  740.11   526.4  744.76
   536.5  745.81   546.7  749.15   576.7  761.16   635.7  780.76   645.6  781.96
   665.2  786.45   694.7  800.31   743.9  821.63   763.5  823.83   783.2  828.63
#Mann= 3 , 0 , 0
       0     .06       0   435.5    .045       0   455.5     .06       0
Bank Sta=435.5,455.5
XS Rating Curve= 0 ,0
Exp/Cntr=0.3,0.1

Type RM Length L Ch R = 1 ,3874.1  ,1049.9,1035,1019.7
XS GIS Cut Line= 4
     1627421.227      269193.999     1627260.897      269324.499
     1627074.468      269574.315     1626917.868      269913.616
#Sta/Elev= 30
     9.8  884.04    29.5  866.57    98.4   816.3   108.3  806.76   118.1  799.42
   147.7  779.94     187  758.13   196.9  751.48   226.8  740.79   236.9  739.54
   277.1  737.97   297.2  734.97   307.3  732.37   317.3  731.42   327.3  731.77
   427.9  738.46   458.1  741.52   498.3  742.88   609.3  748.94   659.8  754.06
   669.9  756.35   700.2  766.81   710.3  767.53   730.5  776.51   750.7  787.96
   801.2  808.87   821.4  813.84   851.7  827.43     882  837.48   892.1  842.05
#Mann= 3 , 0 , 0
       0     .06       0   307.3    .045       0   327.3     .06       0
Bank Sta=307.3,327.3
XS Rating Curve= 0 ,0
Exp/Cntr=0.3,0.1

Type RM Length L Ch R = 1 ,2839.1  ,548.4,547.4,546.8
XS GIS Cut Line= 4
     1626288.669      268725.595     1626246.722      268907.364
     1626224.351      269346.405     1626064.954      269827.392
#Sta/Elev= 30
     9.8  923.69    19.6  921.99    68.7  889.17    88.4  872.73     108  851.91
   117.8  850.14   127.6  843.53   206.5     776   216.5  770.31   226.5  768.44
   256.5   749.6   286.5   736.6   306.4  730.93   346.4   724.9   356.4  724.41
   366.4  724.99   396.4  728.85   606.2  735.12   636.3   742.7   666.7  758.76
     687  766.02   778.2  780.06   828.8  801.84   849.1  806.57   930.2  850.39
   950.5   856.5  1031.5  900.99  1051.8   906.4  1122.7  948.78  1132.9  953.36
#Mann= 3 , 0 , 0
       0      .1       0   346.4    .045       0   366.4     .08       0
Bank Sta=346.4,366.4
XS Rating Curve= 0 ,0
Exp/Cntr=0.3,0.1

Type RM Length L Ch R = 1 ,2291.7  ,569,590.9,612.7
XS GIS Cut Line= 4
      1625824.46      268521.455     1625709.806      268957.699
     1625707.009      269315.644     1625709.806      269757.481
#Sta/Elev= 30
      10  972.46    50.1  954.08    60.1  953.22    70.2  948.78   180.4  897.04
   260.6  864.99   270.6   863.6   290.7  854.04   340.8  827.83   370.9  809.48
     411  780.06   451.1  757.16   520.7  741.04   550.5  737.03   570.4  730.49
   580.3  730.28   600.2  720.69   610.2  720.61   620.2  722.02   789.1  732.53
   889.4  746.69   929.5  767.94   969.7  792.79   989.8   799.7  1080.1  859.59
  1100.2  865.77  1130.4  879.78  1180.6  898.49  1200.7   902.2  1250.9  920.12
#Mann= 3 , 0 , 0
       0      .8       0   600.2    .045       0   620.2     .06       0
Bank Sta=600.2,620.2
XS Rating Curve= 0 ,0
Exp/Cntr=0.3,0.1

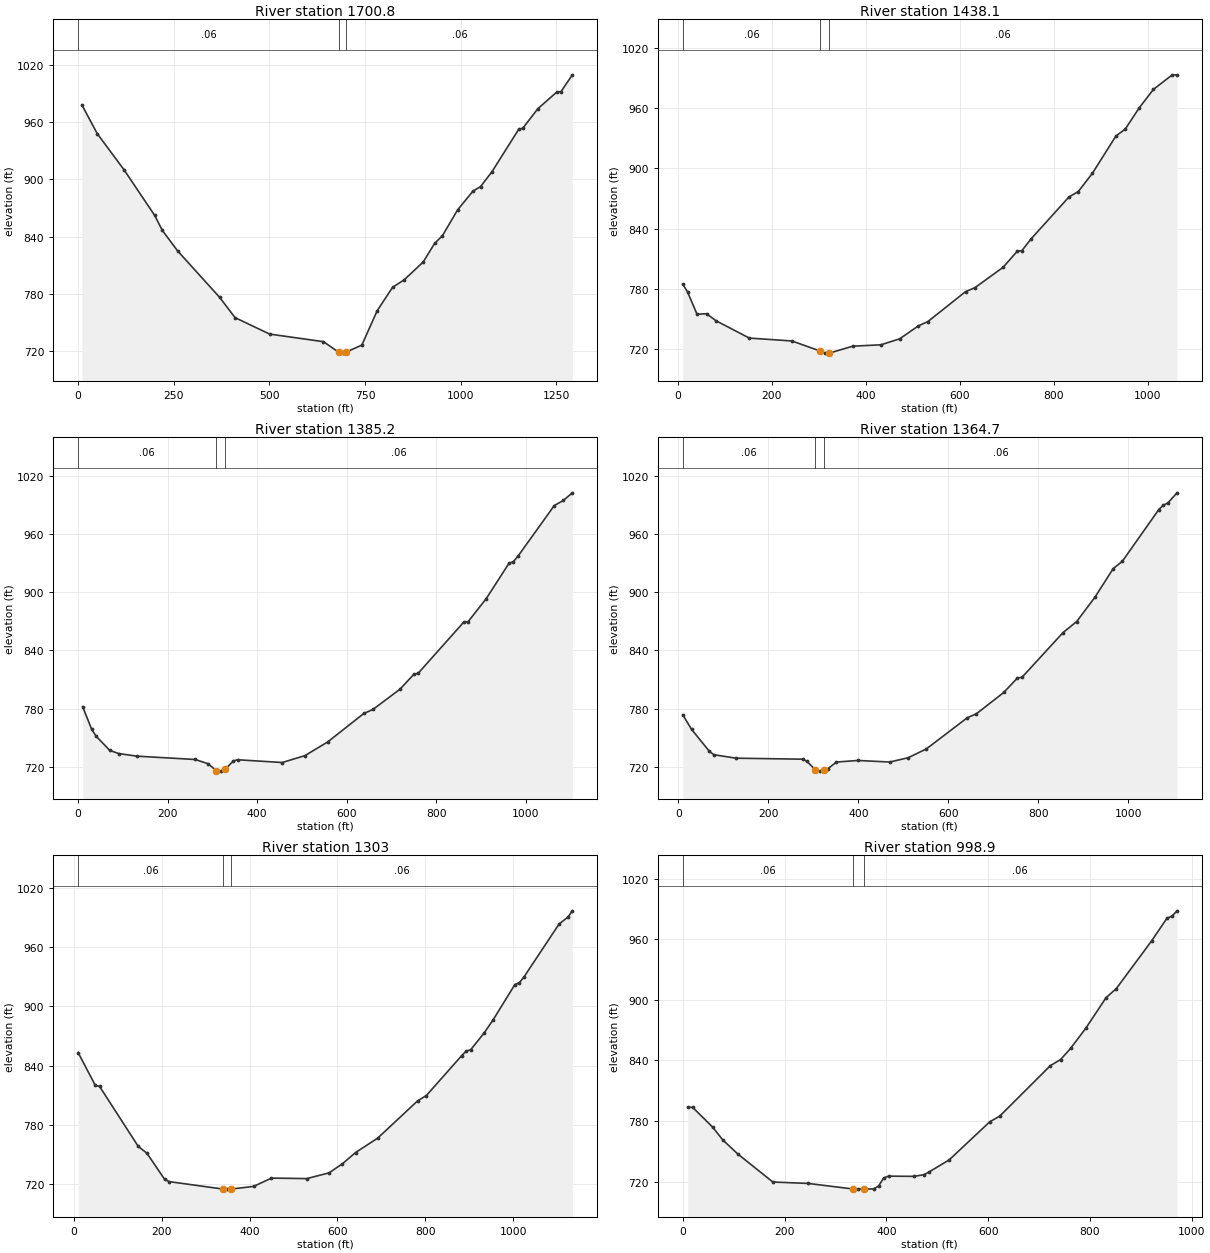
Type RM Length L Ch R = 1 ,1700.8  ,269.6,262.7,255.7
XS GIS Cut Line= 4
     1625799.292       268501.88     1625500.073      268683.649
     1625142.128      268991.257     1625128.146      269461.059
#Sta/Elev= 30
      10   977.9      50  947.84     120     910   200.1  862.18   220.1  846.48
   260.1  824.94   370.2  776.14   410.4  754.95   500.7  737.75   641.3  729.79
   681.5  718.64   691.5  717.78   701.5  718.96   741.7  726.23   781.9  762.31
   822.1  786.78   852.1  794.52   902.1  813.34   932.1  832.87   952.1  840.75
   992.1  867.95  1032.1  887.57  1052.1  892.42  1082.1  908.08  1152.1  952.62
  1162.1  953.36  1202.1  974.17  1252.1  991.72  1262.1  991.78  1292.1 1009.53
#Mann= 3 , 0 , 0
       0     .06       0   681.5    .045       0   701.5     .06       0
Bank Sta=681.5,701.5
XS Rating Curve= 0 ,0
Exp/Cntr=0.3,0.1

Type RM Length L Ch R = 1 ,1438.1  ,50.2,52.9,55.6
XS GIS Cut Line= 4
     1625247.434      268456.113     1625125.889      268630.666
     1625003.653      268812.718     1625123.923      269431.422
#Sta/Elev= 30
    10.1  784.77    20.3  777.06    40.5  754.84    60.8  755.35      81  748.34
   151.9  731.11   242.6  728.25   302.4  718.27   312.4  716.16   322.4  716.19
   372.2  723.09     432  724.43     472  730.41     512  743.33     532  747.55
   612.1  777.27   632.1  781.22   692.1  801.51   722.1  817.38   732.1  818.04
   752.1     830   832.2  871.37   852.2  876.84   882.2  894.97   932.2  931.96
   952.2  938.97   982.2  960.22  1012.2  978.42  1052.3  992.87  1062.3  992.68
#Mann= 3 , 0 , 0
    10.1     .06       0   302.4    .045       0   322.4     .06       0
#XS Ineff= 2 , 0
       0     275             382       0
Permanent Ineff=
       F       F
Bank Sta=302.4,322.4
XS Rating Curve= 0 ,0
Exp/Cntr=0.3,0.1

Type RM Length L Ch R = 1 ,1385.2  ,22.5,20.5,18.6
XS GIS Cut Line= 4
     1625210.523      268430.559     1625067.137       268637.83
     1624981.957      268740.046     1625113.986      269447.039
#Sta/Elev= 30
    10.1   781.9    30.2  758.65    40.3   751.4    70.6   736.8    90.7   733.5
   131.1  730.83   261.5  727.38     290  723.08   308.6  715.93   318.6  715.36
   328.6  717.43   347.1  725.93   356.6   727.1     456  724.26   506.6  731.36
   557.3  745.41   638.3   774.9   658.6  779.01   719.4  800.09   749.8  815.22
   759.9  816.51   861.2  869.04   871.3  869.68   911.8  893.49   962.5   929.9
   972.6  931.78   982.7  937.33  1063.8  989.61    1084  994.88  1104.3 1002.79
#Mann= 3 , 0 , 0
       0     .06       0   308.6    .045       0   328.6     .06       0
Bank Sta=308.6,328.6
XS Rating Curve= 0 ,0
Exp/Cntr=0.3,0.1

Type RM Length L Ch R = 1 ,1364.7  ,77.7,61.7,45.7
XS GIS Cut Line= 4
     1625193.487       268424.88     1625034.484       268639.25
     1624963.501      268738.626     1625102.628        269444.2
#Sta/Elev= 30
     9.9  773.58    29.7  758.36    69.2  735.75    79.1   732.3   128.5  728.71
   276.3  727.69   285.7   725.6   303.9  717.02   313.9  715.35   323.9   716.7
   332.7  717.88   351.4  724.73   399.2  726.35   470.1  724.75   510.6  729.16
   551.1  738.24   642.2  770.48   662.5  774.58   723.3  796.61   753.7  811.57
   763.8  812.25     855  858.45   885.3   869.8   925.9  894.97   966.4  924.48
   986.6  931.95  1067.7  985.43  1077.8  989.95  1087.9  992.28  1108.2 1002.75
#Mann= 3 , 0 , 0
     9.9     .06       0   303.9    .045       0   323.9     .06       0
Bank Sta=303.9,323.9
XS Rating Curve= 0 ,0
Exp/Cntr=0.3,0.1

Type RM Length L Ch R = 1 ,1303    ,319.9,304.1,287.4
XS GIS Cut Line= 4
     1624932.268      268316.986     1624940.786      268483.087
     1624945.045      268786.895     1625089.851      269435.682
#Sta/Elev= 30
     9.8  853.17    48.9  819.91    58.7  818.79   146.8  757.91   166.3  751.13
   206.8   724.5     217  722.25   338.6  714.76   348.6  714.63   358.6  714.73
   409.4   717.4   449.9  725.83   530.6  725.32   580.9  731.13   611.2  740.28
   641.4  751.78   691.7  766.39   782.4  804.13   802.5  809.62   883.1  850.19
   893.2   854.7   903.3  856.01   933.5   872.8   953.6   885.8    1004  922.22
    1014  923.99  1024.1  929.52  1104.7  983.69  1124.8  990.71  1134.9  997.03
#Mann= 3 , 0 , 0
     9.8     .06       0   338.6    .045       0   358.6     .06       0
#XS Ineff= 2 , 0
       0     308             399       0
Permanent Ineff=
       F       F
Bank Sta=338.6,358.6
XS Rating Curve= 0 ,0
Exp/Cntr=0.3,0.1

Type RM Length L Ch R = 1 ,998.9   ,431.3,428.2,415.9
XS GIS Cut Line= 4
     1624537.602      268655.576     1624620.889      268738.863
     1624904.822      268969.795     1625071.396      269427.873
#Sta/Elev= 30
     9.8  793.94    19.6   793.5    58.9  773.98    78.5  761.47     108  747.53
   177.1   719.7   246.4  718.31   335.3  712.76   345.3  712.67   355.3  712.78
     375  712.87   384.9  715.77   394.7  723.68   404.6  725.52   454.1  725.31
   473.9  726.94   483.8  729.59   523.6  741.63   603.1  779.22     623  784.97
   722.5  834.94   742.4   840.9   762.3  852.09   792.1  871.99   831.9   902.2
   851.8  911.07   921.5  958.48   951.3  980.68   961.3  982.84   971.2  988.11
#Mann= 3 , 0 , 0
       0     .06       0   335.3    .045       0   355.3     .06       0
Bank Sta=335.3,355.3
XS Rating Curve= 0 ,0
Exp/Cntr=0.3,0.1

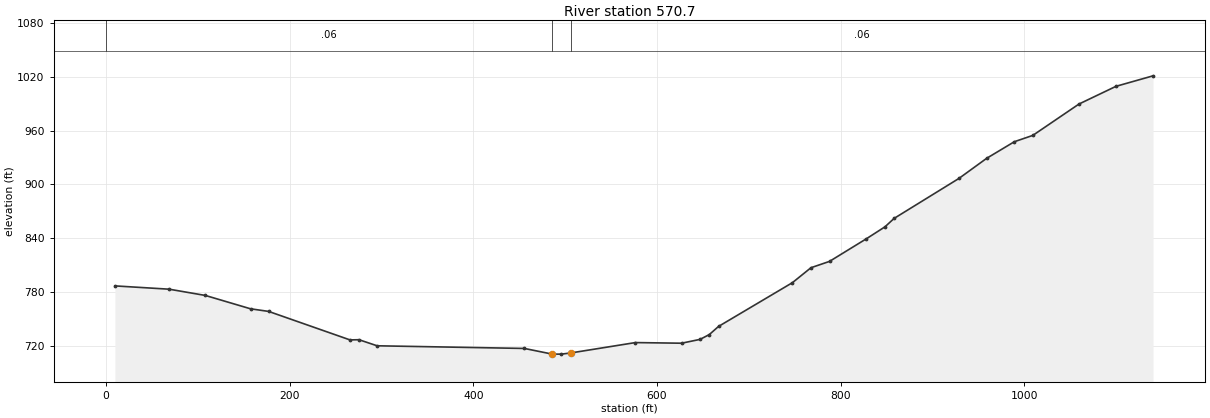
Type RM Length L Ch R = 1 ,570.7   ,561.2,570.7,590.3
XS GIS Cut Line= 4
     1624478.922      268765.363     1624412.671      269083.368
     1624759.016      269245.733     1625122.553      269480.634
#Sta/Elev= 30
     9.8   786.7    68.9  783.01   108.3  776.03   157.5  761.12   177.2   758.2
   265.8  726.38   275.6   726.6   295.3  719.82   455.7  716.85     486  710.52
     496  710.51     506   711.8   576.5   723.4   626.8   722.7   646.9  726.96
     657  732.33   667.1  741.45   747.6  790.36   767.7  806.98   787.9  814.05
   828.1  839.35   848.3  852.65   858.3  862.09   928.8  906.66     959  929.13
   989.2  947.69  1009.3  954.75  1059.6  989.79  1099.9 1009.55  1140.2 1021.25
#Mann= 3 , 0 , 0
       0     .06       0     486    .045       0     506     .06       0
Bank Sta=486,506
XS Rating Curve= 0 ,0
Exp/Cntr=0.3,0.1

Chan Stop Cuts=-1
Use User Specified Reach Order=0